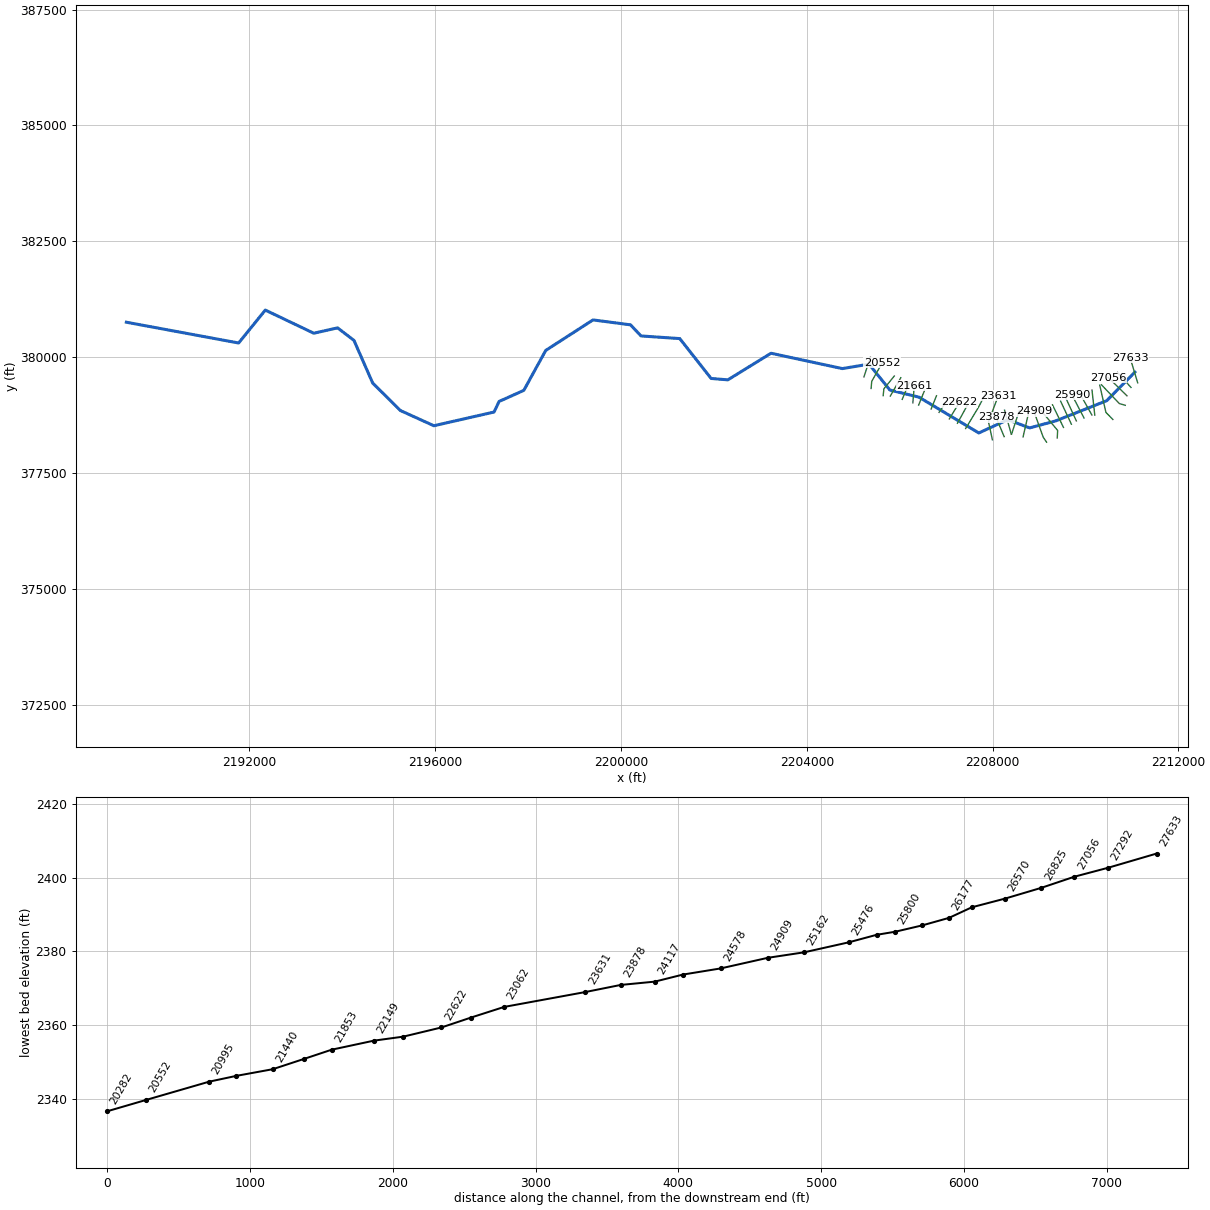
--- SPICERN.prj (project) ---

Proj Title=SPICERN
Current Plan=p01
Default Exp/Contr=0.3,0.1
English Units
Geom File=g01
Flow File=f01
Plan File=p01
Y Axis Title=Elevation
X Axis Title(PF)=Main Channel Distance
X Axis Title(XS)=Station
BEGIN DESCRIPTION:
Stream Name- Spice Run
Flood Zone: Zone A
Greenbrier County, WV
County-Wide Study
WVDHSEM-2018-3, Flood Risk Project
HEC-RAS Version: 5.0.7
General Notes:
For the Hydrology regression was used.
END DESCRIPTION:
DSS Export Rating Curves= 0
DSS Export Rating Curve Sorted= 0
DSS Export Volume Flow Curves= 0
DXF Filename=..\Master\Spice Run\SpiceRun.
DXF OffsetX= 0
DXF OffsetY= 0
DXF ScaleX= 1
DXF ScaleY= 10

--- SPICERN.p01 (plan) ---

Plan Title=Floodplain
Program Version=5.07
Short Identifier=Floodplain
Geom File=g01
Flow File=f01
Subcritical Flow
K Sum by GR= 0
Std Step Tol= 0.01
Critical Tol= 0.01
Num of Std Step Trials= 20
Max Error Tol= 0.3
Flow Tol Ratio= 0.001
Split Flow NTrial= 30
Split Flow Tol= 0.02
Split Flow Ratio= 0.02
Log Output Level= 0
Friction Slope Method= 1
Unsteady Friction Slope Method= 2
Unsteady Bridges Friction Slope Method= 1
Parabolic Critical Depth
Global Vel Dist= 0 , 0 , 0
Global Log Level= 0
CheckData=True
Encroach Param=-1 ,0,0, 0
Computation Interval=1MIN
Output Interval=1HOUR
Instantaneous Interval=1HOUR
Mapping Interval=1HOUR
Computation Time Step Use Courant=        0
Computation Time Step Use Time Series=    0
Computation Time Step Count To Double=0
Computation Time Step Max Doubling=0
Computation Time Step Max Halving=0
Computation Time Step Residence Courant=0
Run HTab= 0
Run UNet= 0
Run Sediment= 0
Run PostProcess= 0
Run WQNet= 0
Run RASMapper=-1
UNET Theta= 1
UNET Theta Warmup= 1
UNET ZTol= 0.02
UNET ZSATol= 0.02
UNET MxIter= 20
UNET Max Iter WO Improvement= 0
UNET MaxInSteps= 0
UNET DtIC= 0
UNET DtMin= 0
UNET MaxCRTS= 20
UNET WFStab= 2
UNET SFStab= 1
UNET WFX= 1
UNET SFX= 1
UNET 1D Methodology=Finite Difference
UNET DSS MLevel= 4
UNET Pardiso=0
UNET DZMax Abort= 100
UNET Use Existing IB Tables=-1
UNET Froude Reduction=False
UNET Froude Limit= 0.8
UNET Froude Power= 4
UNET D1 Cores= 0
UNET D2 Coriolis=0
UNET D2 Cores= 0
UNET D2 Theta= 1
UNET D2 Theta Warmup= 1
UNET D2 Z Tol= 0.01
UNET D2 Volume Tol= 0.01
UNET D2 Max Iterations= 20
UNET D2 Equation= 0
UNET D2 RampUpFraction=0.1
UNET D2 TimeSlices= 1
UNET D2 BCVolumeCheck=0
UNET D1D2 MaxIter= 0
UNET D1D2 ZTol=0.01
UNET D1D2 QTol=0.1
UNET D1D2 MinQTol=1
DSS File=dss
Write IC File= 0
Write IC File at Fixed DateTime=0
Write IC File at Sim End=0
Echo Input=False
Echo Parameters=False
Echo Output=False
Write Detailed= 0
HDF Write Warmup=0
HDF Write Time Slices=0
HDF Flush=0
HDF Face Node Velocities=0
HDF Compression= 1
HDF Chunk Size= 1
HDF Spatial Parts= 1
HDF Use Max Rows=0
HDF Fixed Rows= 1
Calibration Method= 0
Calibration Iterations= 20
Calibration Max Change=0.05
Calibration Tolerance=0.2
Calibration Maximum=1.5
Calibration Minimum=0.5
Calibration Optimization Method= 1
WQ AD Non Conservative
WQ ULTIMATE=-1
WQ Max Comp Step=1HOUR
WQ Output Interval=15MIN
WQ Output Selected Increments= 0
WQ Output face flow=0
WQ Output face velocity=0
WQ Output face area=0
WQ Output face dispersion=0
WQ Output cell volume=0
WQ Output cell surface area=0
WQ Output cell continuity=0
WQ Output cumulative cell continuity=0
WQ Output face conc=0
WQ Output face dconc_dx=0
WQ Output face courant=0
WQ Output face peclet=0
WQ Output face adv mass=0
WQ Output face disp mass=0
WQ Output cell mass=0
WQ Output cell source sink temp=0
WQ Output nsm pathways=0
WQ Output nsm derived pathways=0
WQ Output MaxMinRange=-1
WQ Daily Max Min Mean=-1
WQ Daily Range=0
WQ Daily Time=0
WQ Create Restart=0
WQ Fixed Restart=0
WQ System Summary=0
WQ Write To DSS=0
WQ Use Fixed Temperature=0
Sorting and Armoring Iterations= 10
XS Update Threshold= 0.02
Bed Roughness Predictor= 0
Hydraulics Update Threshold= 0.02
Energy Slope Method= 1
Volume Change Method= 1
Sediment Retention Method= 0
XS Weighting Method= 0
Number of US Weighted Cross Sections= 1
Number of DS Weighted Cross Sections= 1
Upstream XS Weight=0
Main XS Weight=1
Downstream XS Weight=0
Number of DS XS's Weighted with US Boundary= 1
Upstream Boundary Weight= 1
Weight of XSs Associated with US Boundary= 0
Number of US XS's Weighted with DS Boundary= 1
Downstream Boundary Weight= 0.5
Weight of XSs Associated with DS Boundary= 0.5
Percentile Method= 0
Sediment Output Level= 3
Mass or Volume Output= 0
Output Increment Type= 1
Profile and TS Output Increment= 1
XS Output Flag= 0
XS Output Increment= 10
Write Gradation File= 0
Read Gradation Hotstart= 0
Write HDF5 File= 1
Write Binary Output= 1
Write DSS Sediment File= 0
SV Curve= 0
Specific Gage Flag= 0

--- SPICERN.f01 (steady flow) ---

Flow Title=Spice Run Flows
Program Version=5.07
Number of Profiles= 6
Profile Names=f1p,f10p,f4p,f2p,f02p,f1pplus
River Rch & RM=Spice Run,A2              ,27633
     442     231     309     374     621     654
River Rch & RM=Spice Run,A2              ,27056
     590     312     415     499     823     872
River Rch & RM=Spice Run,A2              ,26338
     723     386     511     613    1010    1070
River Rch & RM=Spice Run,A2              ,25476
     808     433     572     686    1120    1200
River Rch & RM=Spice Run,A2              ,23062
     910     490     646     774    1260    1350
River Rch & RM=Spice Run,A2              ,20282
    1190     650     852    1020    1650    1770
River Rch & RM=Spice Run,A2              ,16566
    1340     730     955    1140    1840    1980
River Rch & RM=Spice Run,A2              ,10376
    1490     817    1070    1270    2040    2200
River Rch & RM=Spice Run,A2              ,6590
    1660     912    1190    1420    2270    2450
River Rch & RM=SPICERN,Main            ,27633
     442     231     309     374     621     654
River Rch & RM=SPICERN,Main            ,27056
     590     312     415     499     823     872
River Rch & RM=SPICERN,Main            ,26338
     723     386     511     613    1010    1070
River Rch & RM=SPICERN,Main            ,25476
     808     433     572     686    1120    1200
River Rch & RM=SPICERN,Main            ,23062
     910     490     646     774    1260    1350
River Rch & RM=SPICERN,Main            ,20282
    1190     650     852    1020    1650    1770
River Rch & RM=SPICERN,Main            ,16566
    1340     730     955    1140    1840    1980
River Rch & RM=SPICERN,Main            ,10376
    1490     817    1070    1270    2040    2200
River Rch & RM=SPICERN,Main            ,6590
    1660     912    1190    1420    2270    2450
Boundary for River Rch & Prof#=SPICERN,Main            , 1
Up Type= 0
Dn Type= 3
Dn Slope=0.026
Boundary for River Rch & Prof#=SPICERN,Main            , 2
Up Type= 0
Dn Type= 3
Dn Slope=0.026
Boundary for River Rch & Prof#=SPICERN,Main            , 3
Up Type= 0
Dn Type= 3
Dn Slope=0.026
Boundary for River Rch & Prof#=SPICERN,Main            , 4
Up Type= 0
Dn Type= 3
Dn Slope=0.026
Boundary for River Rch & Prof#=SPICERN,Main            , 5
Up Type= 0
Dn Type= 3
Dn Slope=0.026
Boundary for River Rch & Prof#=SPICERN,Main            , 6
Up Type= 0
Dn Type= 3
Dn Slope=0.026
DSS Import GetInterval= 0
DSS Import GetPeak= 0
DSS Import FillOption= 0

--- SPICERN.g01 (geometry) ---

Geom Title=Spice Run
Program Version=5.07

River Reach=SPICERN         ,Main
Reach XY= 30
2211066.36977275379681.0461466462210459.70267899 379063.91221033
2209356.91912337378626.2841485742208799.71551342378476.600720897
2208327.45759968378653.2922966632207704.92669247378367.406385481
2206415.03524338379139.8507067412205789.59128432379293.238195241
2205341.71521159379851.6685088132204765.07660107379755.831430137
 2203230.1324925380086.9396918122202300.67044063379512.929028809
2201940.29747374379543.0759501462201265.22533305380402.936763227
 2200430.9940619380459.9786439092200204.80455367380699.745880887
2199397.33143108380805.6570864022198379.03195848380147.749281481
2197906.83605249 379285.839916082197373.83974315379046.561523229
2197266.34914447378818.4665069732195970.27758963378523.244984567
2195250.18813179378851.1641983392194653.16703488379443.216241732
2194250.05563642380363.7367104142193896.88737951380634.225998819
2193384.00421892380518.9404682372192340.25269751381017.927659228
2191766.25220506 380307.810641142189348.51900001380755.968999997

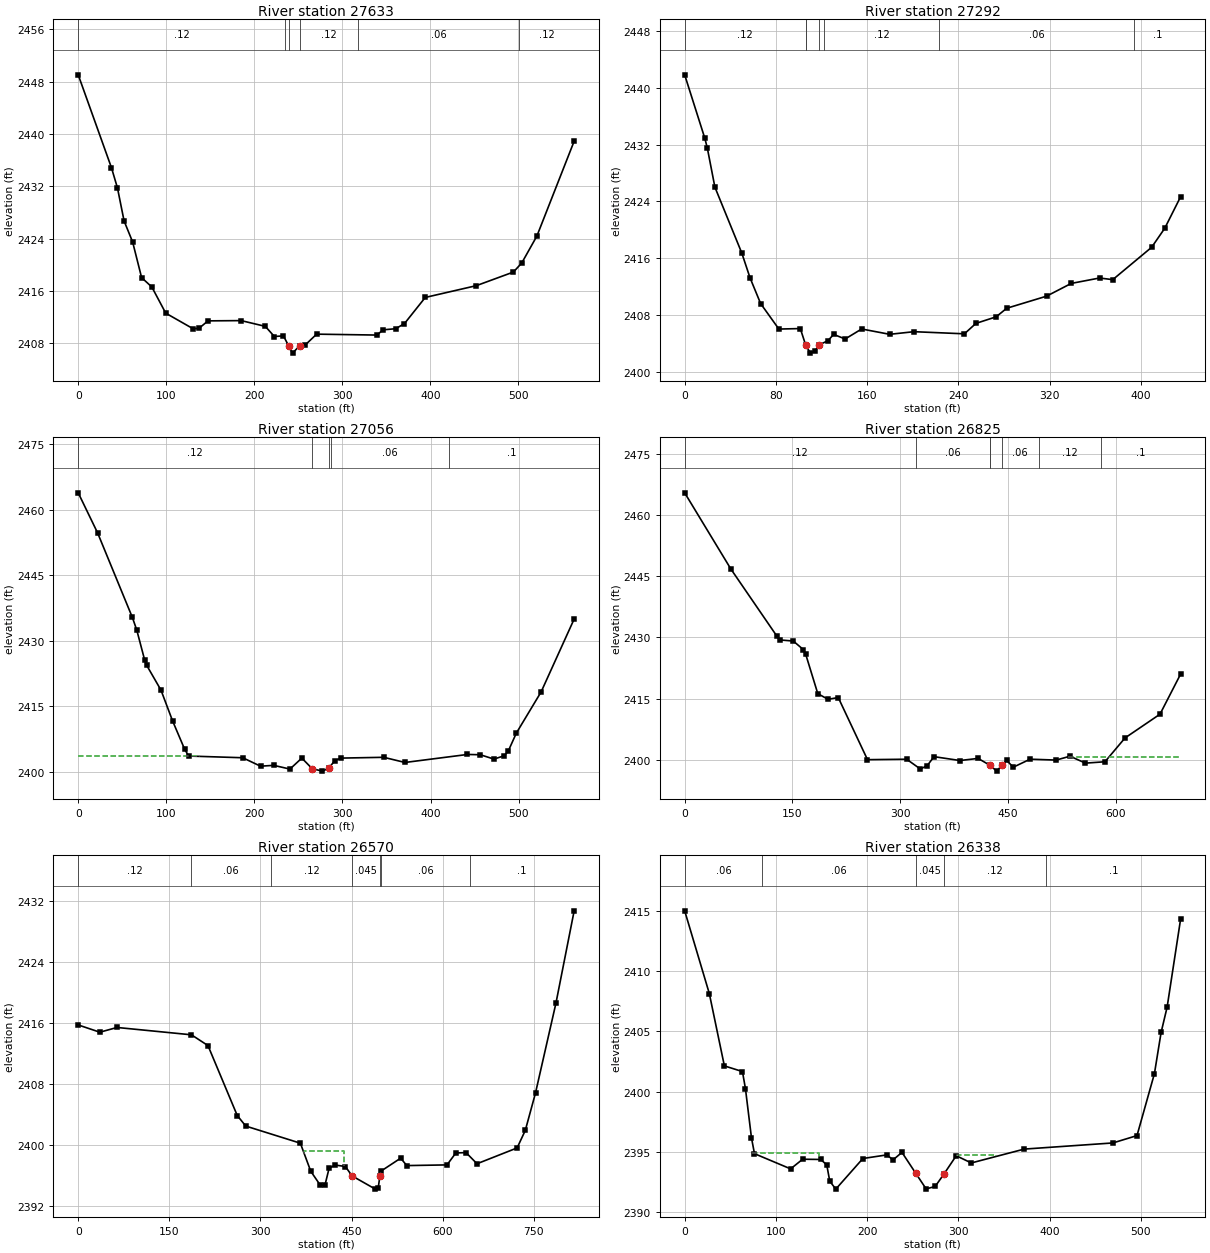
Type RM Length L Ch R = 1 ,27633   ,340.1,341.2,345.9
XS GIS Cut Line= 2
 2211126.2670434379448.0451389012210963.50329316379987.351893433
#Sta/Elev= 30
       0 2449.04    37.8 2434.83    44.6 2431.74    52.1 2426.71    61.8  2423.5
      72 2418.05    83.6 2416.62    99.4 2412.62   130.3 2410.25   137.1 2410.29
   147.4 2411.44   185.1 2411.48   212.5  2410.6   222.8 2409.05   233.1 2409.15
     239 2407.62   243.4 2406.51   251.52407.624   257.4  2407.7   270.8 2409.41
   339.3 2409.27   346.2 2410.07   360.6 2410.24   370.6 2411.03   394.2 2415.02
   452.2 2416.82   494.3  2418.9   503.8 2420.29     521 2424.41   563.3  2438.9
#Mann= 6 ,-1 , 0
       0     .12       0  235.02     .12       0     239    .045       0
   251.5     .12       0  317.79     .06       0     501     .12       0
#XS Ineff= 2 , 0
          161.34 2411.34
Permanent Ineff=
       F       F
Bank Sta=239,251.5
XS Rating Curve= 0 ,0
Exp/Cntr=0.3,0.1

Type RM Length L Ch R = 1 ,27292   ,231.4,235.6,236.5
XS GIS Cut Line= 2
 2210981.1719202379349.5910166972210691.23241612379673.792608314
#Sta/Elev= 30
       0 2441.84    17.7 2432.88    19.9 2431.49    26.5 2426.02    50.1 2416.73
    57.3 2413.25    66.6 2409.62    82.6 2406.03   101.4  2406.1   106.12403.782
   110.2 2402.64   114.6 2402.97   117.5 2403.77   125.7  2404.4   130.6 2405.28
   140.7 2404.63   155.2 2406.04   179.8 2405.29   201.1 2405.66   245.3 2405.36
   255.4 2406.83   273.1 2407.75   282.4 2408.96   317.3 2410.66     339 2412.46
   363.8 2413.22   375.4 2412.99   409.5 2417.55     421 2420.23   434.9 2424.67
#Mann= 7 ,-1 , 0
       0     .12       0  106.07     .12       0   106.1    .045       0
   117.5     .12       0  122.27     .12       0  223.15     .06       0
  394.26      .1       0
Bank Sta=106.1,117.5
XS Rating Curve= 0 ,0
Exp/Cntr=0.3,0.1

Type RM Length L Ch R = 1 ,27056   ,231.8,231.6,231.3
XS GIS Cut Line= 2
2210895.13687761379168.5921696092210493.23389474379562.936275173
#Sta/Elev= 30
       0 2463.86    22.1 2454.66    61.5 2435.36    66.5 2432.47    75.4 2425.66
    77.7 2424.43      94 2418.73   107.1 2411.73   120.9 2405.19   125.5 2403.67
   186.8 2403.28     207 2401.35     222 2401.54   240.4 2400.69   253.9  2403.2
   265.7 2400.77   277.2 2400.22   284.2 2400.85   291.4 2402.62   298.1  2403.2
   346.9 2403.38     371  2402.2     442 2404.03   456.5 2403.97   472.1 2402.97
   483.4 2403.72   488.1 2404.73   497.5 2408.93   525.6 2418.34   563.1    2435
#Mann= 5 ,-1 , 0
       0     .12       0   265.7    .045       0   284.2     .06       0
  287.03     .06       0  420.94      .1       0
#XS Ineff= 2 , 0
          138.71 2403.72  449.09         2403.89
Permanent Ineff=
       F       F
Bank Sta=265.7,284.2
XS Rating Curve= 0 ,0
Exp/Cntr=0.3,0.1

Type RM Length L Ch R = 1 ,26825   ,271.1,254.8,245.4
XS GIS Cut Line= 3
 2210857.3212054378964.0843034522210730.24934334379002.185078537
2210345.89394636379406.298423425
#Sta/Elev= 30
       0 2465.47    64.3 2446.78   128.4  2430.3   132.7 2429.38   151.2 2429.11
   165.1 2427.03   168.5 2425.86   185.3 2416.21   199.5 2414.82   213.8 2415.25
   254.5 2400.01     309 2400.12   328.1 2397.72   337.6 2398.54   347.1 2400.75
   383.2  2399.8   408.5 2400.32   425.42398.587   434.3  2397.2   441.4 2398.59
   448.2 2399.81   457.5 2398.17   480.9 2400.13   517.1 2399.91   536.4 2400.86
   557.9 2399.16   585.1  2399.5     613 2405.34   661.7 2411.17   690.4 2421.01
#Mann= 7 ,-1 , 0
       0     .12       0  321.65     .06       0  425.29     .06       0
   425.4    .045       0   441.4     .06       0  493.01     .12       0
  579.34      .1       0
#XS Ineff= 2 , 0
                          533.55         2400.78
Permanent Ineff=
       F       F
Bank Sta=425.4,441.4
XS Rating Curve= 0 ,0
Exp/Cntr=0.3,0.1

Type RM Length L Ch R = 1 ,26570   ,231,232.1,227.4
XS GIS Cut Line= 3
2210591.65914489378658.3012036882210442.00939789 378810.64607689
2210308.79284507379398.592187082
#Sta/Elev= 30
       0 2415.75    35.6  2414.8    63.9 2415.42   186.4 2414.46   213.6 2413.05
   261.8  2403.9   275.8 2402.52   365.7 2400.28   382.8 2396.61   398.7 2394.76
   406.3 2394.83     413    2397   423.1 2397.42   439.8 2397.23   450.8    2396
   489.2 2394.27   493.8 2394.41   496.7 2396.01   498.5 2396.63   530.8 2398.32
   540.9 2397.35   607.1 2397.44   621.6    2399   638.4 2399.05   656.5 2397.59
   722.5 2399.66     736 2401.96   752.8 2406.86   786.4 2418.59   816.4 2430.68
#Mann= 7 ,-1 , 0
       0     .12       0  185.68     .06       0   317.1     .12       0
   450.8    .045       0   496.7      .1       0   498.5     .06       0
  645.24      .1       0
#XS Ineff= 3 ,-1
   372.1  438.26 2399.22  530.89  629.54 2398.22  629.54   735.4 2399.01
Permanent Ineff=
       F       F       F
Bank Sta=450.8,496.7
XS Rating Curve= 0 ,0
Exp/Cntr=0.3,0.1

Type RM Length L Ch R = 1 ,26338   ,155.3,160.3,168.3
XS GIS Cut Line= 2
2210201.87031063378752.001453512 2210142.2030948379292.195205197
#Sta/Elev= 30
       0    2415      27 2408.14    43.5 2402.14    63.3 2401.67    66.6 2400.25
    73.2 2396.17    76.5 2394.86   116.1  2393.6   129.3  2394.4   149.1 2394.38
   155.7 2393.93     159 2392.58   165.6 2391.92   195.3 2394.46   221.7 2394.76
   228.3 2394.34   238.1 2394.97     253 2393.26   264.6 2391.94   274.5 2392.14
   284.4  2393.2   297.6 2394.69   314.1 2394.09   372.1 2395.24   469.3 2395.75
   495.7 2396.36   514.8  2401.5   522.1 2404.91   528.7 2407.01   543.5 2414.32
#Mann= 5 ,-1 , 0
       0     .06       0      85     .06       0     253    .045       0
   284.4     .12       0  396.34      .1       0
#XS Ineff= 2 ,-1
    73.5  147.08 2394.88  297.97  341.28 2394.72
Permanent Ineff=
       F       F
Bank Sta=253,284.4
XS Rating Curve= 0 ,0
Exp/Cntr=0.3,0.1

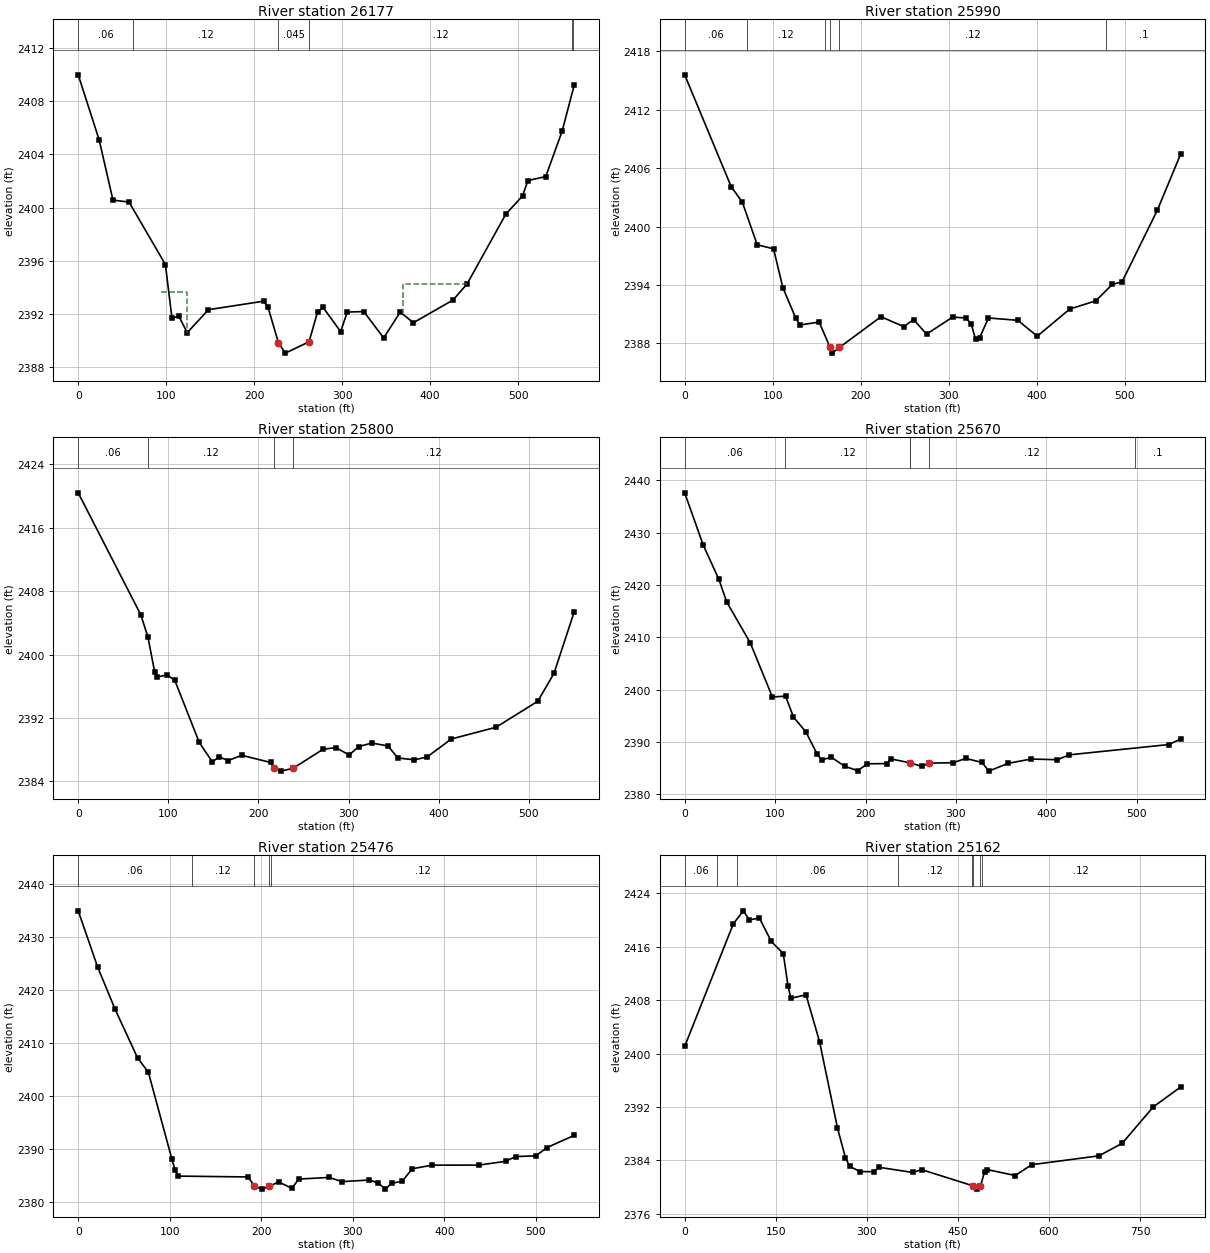
Type RM Length L Ch R = 1 ,26177   ,184.3,187.7,190.9
XS GIS Cut Line= 2
 2210139.5344773378754.6305557592209864.54252229379246.685916316
#Sta/Elev= 30
       0 2409.99    23.9 2405.07    39.5 2400.56    57.8 2400.41    99.1 2395.71
   106.6 2391.65   114.2 2391.84   123.9 2390.58     148 2392.31   210.7 2392.95
   215.6 2392.53   227.5 2389.83   235.4 2389.04   262.3 2389.89     272 2392.12
   278.2 2392.49   298.3 2390.66   305.8 2392.13   324.6 2392.17   347.2 2390.18
     366 2392.13     381 2391.33   426.1 2393.04   442.1 2394.26   486.2 2399.52
     505 2400.87   511.1 2402.03   531.4 2402.33   550.1 2405.76   563.7  2409.2
#Mann= 6 ,-1 , 0
       0     .06       0   62.13     .12       0   227.5    .045       0
   262.3     .12       0  561.15      .1       0  562.49      .1       0
#XS Ineff= 2 ,-1
   93.92     124 2393.62  369.41  441.59 2394.25
Permanent Ineff=
       F       F
Bank Sta=227.5,262.3
XS Rating Curve= 0 ,0
Exp/Cntr=0.3,0.1

Type RM Length L Ch R = 1 ,25990   ,186.5,189.4,190.4
XS GIS Cut Line= 2
2209970.96766249378689.3012791052209710.19026967379188.921275177
#Sta/Elev= 30
       0 2415.58    52.9 2404.08    65.4 2402.53    82.4 2398.13     101 2397.71
   111.6 2393.72   126.2  2390.6   131.1 2389.89   152.8 2390.19   165.12387.622
   167.6    2387   175.82387.578   223.1 2390.74     249 2389.72   260.1 2390.45
   274.9 2388.95   304.5  2390.7   319.3 2390.61   325.6 2390.02   330.6  2388.4
   335.3  2388.6   345.2 2390.61   378.5 2390.37   400.7 2388.74   437.5 2391.52
   467.4 2392.38   486.1 2394.07     497 2394.31   537.2 2401.69   563.6 2407.43
#Mann= 6 ,-1 , 0
       0     .06       0   70.85     .12       0  159.76     .12       0
   165.1    .045       0   175.8     .12       0  478.82      .1       0
Bank Sta=165.1,175.8
XS Rating Curve= 0 ,0
Exp/Cntr=0.3,0.1

Type RM Length L Ch R = 1 ,25800   ,130.3,130.4,130.3
XS GIS Cut Line= 2
2209804.95694829 378627.037480032209575.75519962379127.231220715
#Sta/Elev= 30
       0 2420.42    69.5    2405    77.4 2402.18    84.8 2397.81    87.3 2397.15
    98.4 2397.43   107.1 2396.76   134.3  2388.9   148.9 2386.43   156.1 2387.08
   166.5 2386.62   181.4 2387.28   213.5 2386.37   217.5 2385.66   224.7 2385.28
   238.3 2385.63   271.6 2388.04     286 2388.25   300.5 2387.32   311.3 2388.38
   325.7 2388.83   343.8 2388.45   354.6 2386.94   372.7 2386.71   386.8 2387.05
     414 2389.34   463.5 2390.82   509.8  2394.1   527.8 2397.62   550.2 2405.37
#Mann= 4 ,-1 , 0
       0     .06       0   77.23     .12       0   217.5    .045       0
   238.3     .12       0
Bank Sta=217.5,238.3
XS Rating Curve= 0 ,0
Exp/Cntr=0.3,0.1

Type RM Length L Ch R = 1 ,25670   ,194.2,194.3,195.6
XS GIS Cut Line= 2
2209698.35373712 378556.376743292209465.90748573379053.084349999
#Sta/Elev= 30
       0 2437.61    20.5 2427.63    37.8 2421.09    46.4 2416.78    72.4 2408.99
      97  2398.6   111.6 2398.77   120.2  2394.8   134.1 2391.91   146.4 2387.73
   151.3  2386.6   162.3 2387.08   176.8 2385.38   191.3 2384.53   202.1 2385.84
   223.9 2385.88   227.8 2386.78   249.2 2386.02   262.4 2385.33   269.8 2385.96
   296.9 2386.05   310.8 2386.86   328.9  2386.1   336.2 2384.44   357.9 2385.94
   383.1 2386.75   412.2 2386.62   425.2 2387.55   535.4 2389.52   548.4 2390.57
#Mann= 6 ,-1 , 0
       0     .06       0  111.03     .12       0  249.19     .12       0
   249.2    .045       0   269.8     .12       0  497.89      .1       0
Bank Sta=249.2,269.8
XS Rating Curve= 0 ,0
Exp/Cntr=0.3,0.1

Type RM Length L Ch R = 1 ,25476   ,312.8,313.5,313.2
XS GIS Cut Line= 2
2209528.14238096 378486.82294185  2209291.263409378974.045267063
#Sta/Elev= 30
       0 2434.99    21.2 2424.38    40.1 2416.46    64.9 2407.18    76.6 2404.51
   102.2 2388.17   105.8 2386.04   109.4 2384.87   185.7 2384.71   192.4 2382.98
   200.6 2382.41   208.4 2382.92   218.9 2383.78   233.5 2382.56   240.8 2384.31
   274.1 2384.62   288.2 2383.83   318.2 2384.13   327.5 2383.59   335.6 2382.44
   342.5 2383.53   353.9 2383.89     365 2386.26   386.7 2386.94   437.8 2386.95
   466.9 2387.67   477.9 2388.57   499.8 2388.69   512.2 2390.27   541.8 2392.56
#Mann= 5 ,-1 , 0
       0     .06       0  123.77     .12       0   192.4    .045       0
   208.4     .12       0  210.24     .12       0
Bank Sta=192.4,208.4
XS Rating Curve= 0 ,0
Exp/Cntr=0.3,0.1

Type RM Length L Ch R = 1 ,25162   ,256.4,253.1,247.9
XS GIS Cut Line= 3
2209394.10207239378259.0203934222209402.32704595378421.206275176
2208984.68114397378925.038169407
#Sta/Elev= 30
       0 2401.07    80.2 2419.46    96.7 2421.39   106.5 2420.03     123 2420.31
   142.7  2416.8   162.4 2414.99   170.1 2410.19   174.7 2408.29   199.9  2408.8
   222.1 2401.79   251.6 2388.88   264.7 2384.41   271.9 2383.09   288.9 2382.32
   311.5  2382.3   320.1 2382.96   375.5 2382.19   390.1 2382.61   475.3 2380.17
     482 2379.69     487 2380.11     494  2382.3   498.1 2382.62   544.4 2381.73
   571.5 2383.35   682.3 2384.68   720.6 2386.56   771.8 2392.01   816.8 2394.99
#Mann= 8 ,-1 , 0
       0     .06       0   53.91     .12       0   86.55     .06       0
  351.58     .12       0  473.74     .12       0   475.3    .045       0
     487     .12       0  489.75     .12       0
Bank Sta=475.3,487
XS Rating Curve= 0 ,0
Exp/Cntr=0.3,0.1

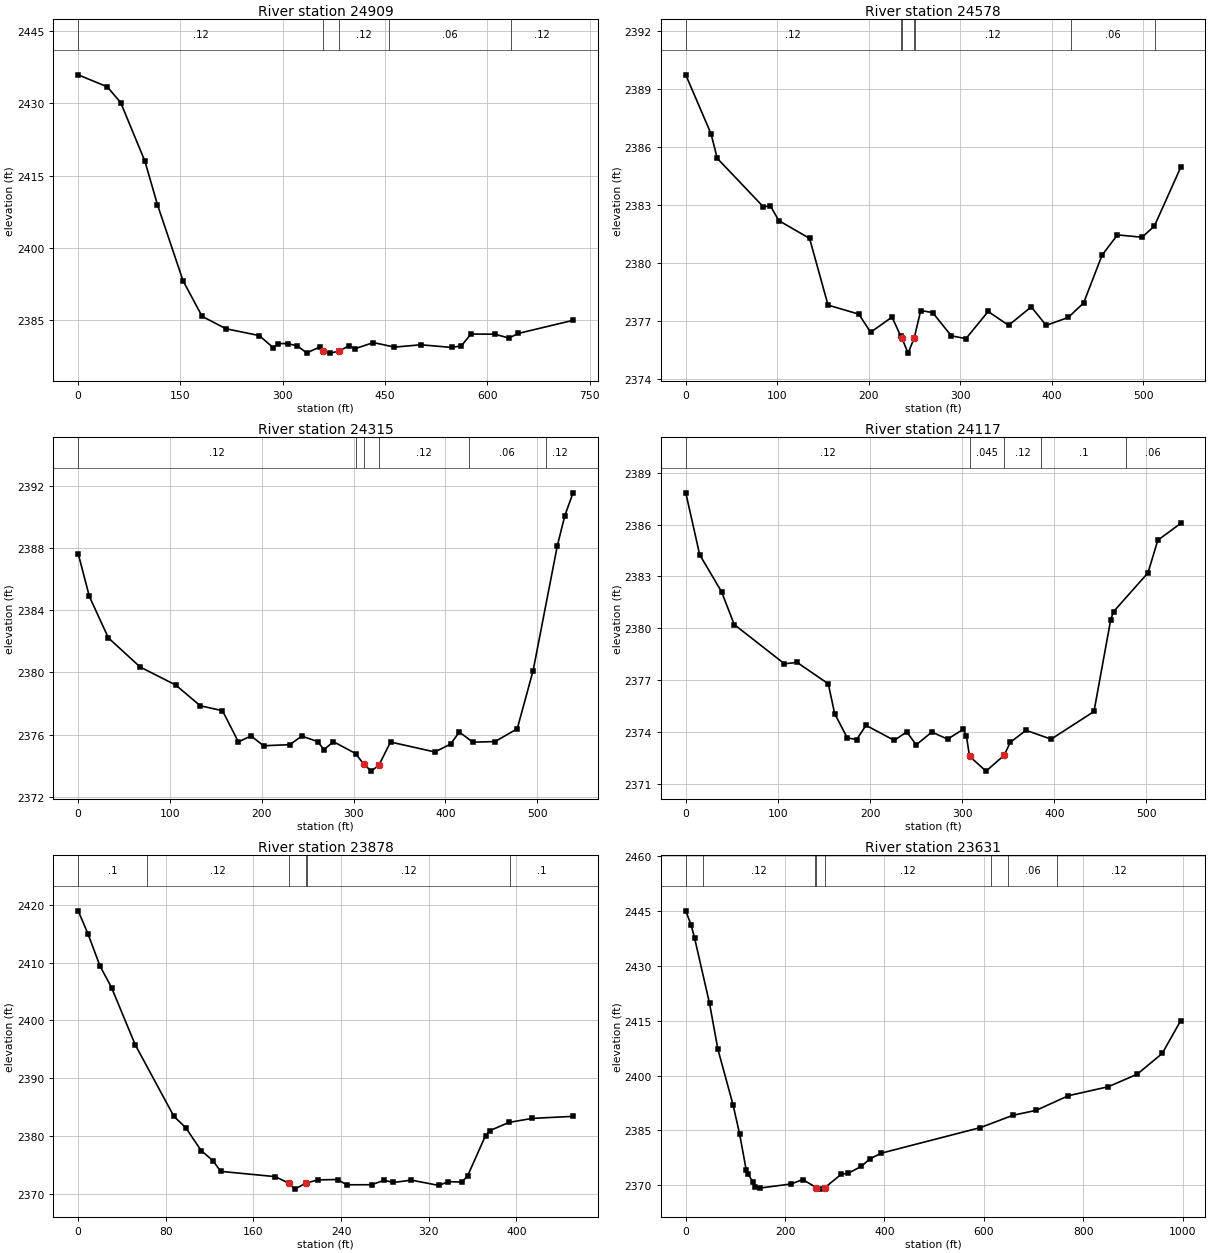
Type RM Length L Ch R = 1 ,24909   ,335.5,331.6,324.4
XS GIS Cut Line= 3
2209163.42332578378169.4366976212209091.35573639378276.478264211
 2208889.5369773378837.710184313
#Sta/Elev= 30
       0 2435.91    42.5 2433.44    62.3 2430.17    97.8 2418.02   116.3 2408.96
   153.7 2393.24   181.7 2385.83   216.6 2383.27   265.4 2381.85   286.3  2379.3
   293.3 2380.19   307.2 2380.19   321.2  2379.7   335.1 2378.26   353.8 2379.45
   358.9 2378.59   369.1 2378.21   382.7 2378.63   397.3 2379.78   405.5 2379.11
   432.8  2380.4   463.7 2379.46   502.5 2379.94   547.8 2379.38   561.8 2379.72
   575.7 2382.16   610.6 2382.14   631.5 2381.34   645.4  2382.3   725.5 2385.01
#Mann= 5 ,-1 , 0
       0     .12       0   358.9    .045       0   382.7     .12       0
  455.47     .06       0  633.97     .12       0
Bank Sta=358.9,382.7
XS Rating Curve= 0 ,0
Exp/Cntr=0.3,0.1

Type RM Length L Ch R = 1 ,24578   ,261.9,263,261.4
XS GIS Cut Line= 2
2208658.29094727378282.6950747662208778.34989276378810.109155147
#Sta/Elev= 30
       0 2389.75    27.7 2386.68    34.4 2385.42    84.9  2382.9    92.4 2382.96
   101.7 2382.19   135.3 2381.27   155.5 2377.81   189.2 2377.34     202  2376.4
   225.4 2377.19   234.9 2376.21   236.3 2376.09     243 2375.32   249.7 2376.11
   256.8 2377.53   269.9 2377.42   290.1 2376.22   306.2 2376.07   330.5 2377.48
   352.8 2376.76   377.6 2377.72   393.9 2376.76     418 2377.17   434.8 2377.92
     455  2380.4   471.8 2381.45   498.7 2381.33   512.2 2381.91   540.9 2384.95
#Mann= 7 ,-1 , 0
       0     .12       0   234.9     .12       0   236.3    .045       0
   249.7     .12       0   250.9     .12       0  421.27     .06       0
   512.6     .12       0
Bank Sta=236.3,249.7
XS Rating Curve= 0 ,0
Exp/Cntr=0.3,0.1

Type RM Length L Ch R = 1 ,24315   ,190.2,197.8,207.6
XS GIS Cut Line= 2
2208410.29571839 378340.696554052208577.92611774378852.973751283
#Sta/Elev= 30
       0 2387.64    12.2 2384.88    32.9 2382.22    67.5 2380.35   106.3 2379.19
     133 2377.86   157.2 2377.54   174.5 2375.54   188.3 2375.92   201.9 2375.29
   230.5 2375.36   243.5 2375.91   260.8 2375.56   267.7 2375.04     278 2375.55
   302.2 2374.79   311.1  2374.1   319.4 2373.66   327.8 2374.07   340.2 2375.53
   388.5 2374.89   405.7  2375.4   415.1 2376.17   429.9 2375.52   454.1 2375.56
   478.2 2376.38   495.5 2380.12   521.8 2388.12     530 2390.07     539 2391.54
#Mann= 6 ,-1 , 0
       0     .12       0  302.82     .12       0   311.1    .045       0
   327.8     .12       0  425.41     .06       0  509.35     .12       0
Bank Sta=311.1,327.8
XS Rating Curve= 0 ,0
Exp/Cntr=0.3,0.1

Type RM Length L Ch R = 1 ,24117   ,233.1,239.1,248.9
XS GIS Cut Line= 2
2208403.63626573378341.0375204072208259.46571678378858.536832156
#Sta/Elev= 30
       0 2387.84    15.1 2384.26    38.9 2382.11    52.6 2380.22   107.1 2377.95
   120.8 2378.03   154.7 2376.79   161.6 2375.07   175.2 2373.67   185.4 2373.56
   195.6 2374.39   226.3 2373.52   239.9 2374.01   250.1 2373.26   267.1    2374
   284.2 2373.59   301.2 2374.16   304.6 2373.78     308  2372.6   325.9 2371.74
   345.5 2372.65   352.3 2373.41   369.3  2374.1   396.6 2373.59   443.1 2375.19
   461.3 2380.51   464.4 2380.97   501.7 2383.21   512.4  2385.1   537.2 2386.07
#Mann= 5 ,-1 , 0
       0     .12       0     308    .045       0   345.5     .12       0
  385.71      .1       0  477.75     .06       0
Bank Sta=308,345.5
XS Rating Curve= 0 ,0
Exp/Cntr=0.3,0.1

Type RM Length L Ch R = 1 ,23878   ,248.2,246.6,245.5
XS GIS Cut Line= 2
2208250.51513209378288.0994175532208076.12068414378704.865999159
#Sta/Elev= 30
       0 2418.95     9.1 2414.91    19.8 2409.47    30.5 2405.67    52.1  2395.8
    87.4 2383.42    98.1 2381.49   112.3  2377.5     123 2375.77   130.1 2373.91
   179.9    2373   192.72371.829   197.6 2370.84   208.3  2371.9     219 2372.44
   236.8  2372.5   245.2 2371.59   267.8  2371.6   279.4 2372.37   287.8 2371.99
   304.3 2372.39   329.2 2371.48     338 2372.13   350.4 2372.06   355.5 2373.12
   371.9  2380.1   375.6 2380.93   393.2 2382.37   414.6 2383.07   451.8 2383.42
#Mann= 6 ,-1 , 0
       0      .1       0   62.83     .12       0   192.7    .045       0
   208.3     .12       0  208.95     .12       0  394.51      .1       0
Bank Sta=192.7,208.3
XS Rating Curve= 0 ,0
Exp/Cntr=0.3,0.1

Type RM Length L Ch R = 1 ,23631   ,573.1,569.1,557.2
XS GIS Cut Line= 3
2207997.37387382378220.2759429032207913.22796495378608.052401904
2208123.80430529379169.236275177
#Sta/Elev= 30
       0  2445.1    10.9 2441.14    17.6 2437.72    47.8 2419.78    64.6 2407.23
    95.1 2392.03   108.2 2384.14   121.7 2374.14     125 2373.03   135.1 2370.98
   138.5 2369.56   148.5  2369.2   212.3 2370.34   235.3 2371.54   262.9 2369.34
   269.4 2368.92   279.5 2369.28     313 2372.99   326.5 2373.25   353.3 2375.14
   370.5 2377.18   393.6 2378.76   593.2 2385.77   658.3 2389.12   705.3 2390.49
   770.4  2394.5   850.5 2396.95   908.6 2400.37     959 2406.05   996.2 2415.01
#Mann= 8 ,-1 , 0
       0      .1       0   34.05     .12       0  260.75     .12       0
   262.9    .045       0   279.5     .12       0  615.06      .1       0
  648.61     .06       0  746.52     .12       0
Bank Sta=262.9,279.5
XS Rating Curve= 0 ,0
Exp/Cntr=0.3,0.1

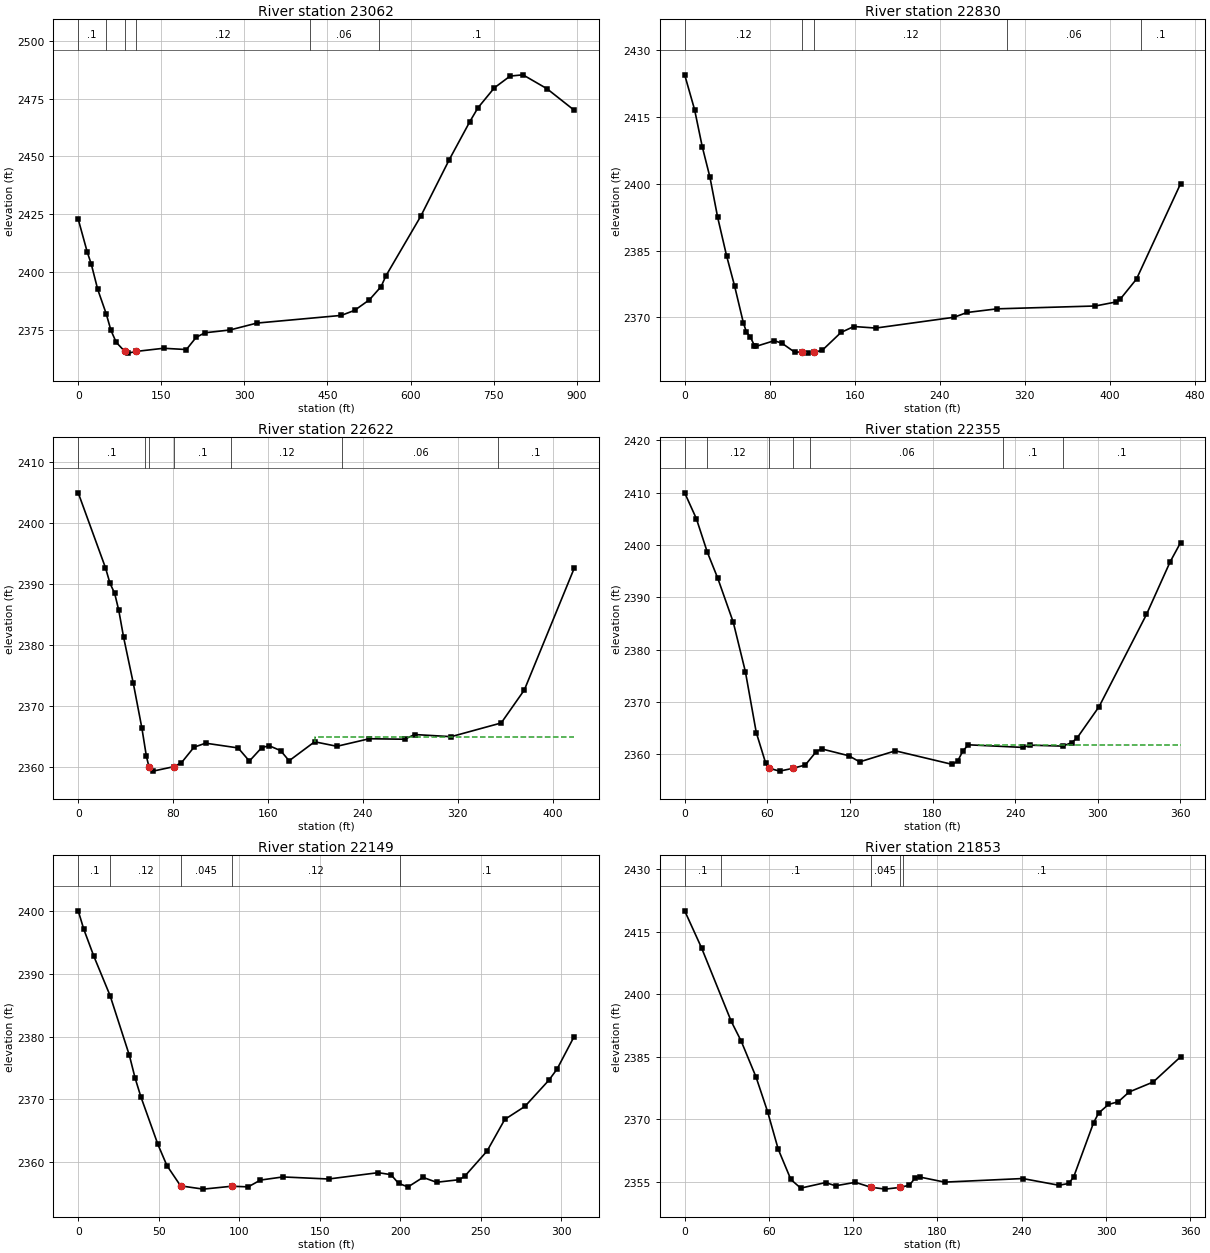
Type RM Length L Ch R = 1 ,23062   ,230.3,231.6,228
XS GIS Cut Line= 3
2207421.22869564 378463.277387642207695.02800351 378916.73376288
2207863.34119849379241.414608514
#Sta/Elev= 30
       0 2422.83    16.1 2408.79    23.7 2403.29    35.2 2392.47    50.5 2381.93
    59.1 2374.73    68.6 2369.57    83.92365.658    90.1 2364.88     105 2365.63
     154 2366.98   195.3 2366.43   212.9  2371.7   228.7 2373.68   274.1  2374.9
   322.6 2377.88   474.9  2381.2   498.9 2383.37   525.7 2387.94   546.9 2393.68
   555.4 2398.25   618.3 2424.04     670 2448.62     707 2465.02   721.7 2471.02
   751.3 2479.66   779.8 2484.75     803 2485.29   846.2  2479.3   895.4 2469.99
#Mann= 6 ,-1 , 0
       0      .1       0   49.85     .12       0    83.9    .045       0
     105     .12       0  417.93     .06       0  542.34      .1       0
Bank Sta=83.9,105
XS Rating Curve= 0 ,0
Exp/Cntr=0.3,0.1

Type RM Length L Ch R = 1 ,22830   ,207.7,208,204
XS GIS Cut Line= 2
2207244.85338186378576.9266050882207468.93614397378986.138434899
#Sta/Elev= 30
       0  2424.4     9.3 2416.61    16.5 2408.32    23.8  2401.4      31 2392.47
    39.4 2383.84    46.9  2377.1    55.2  2368.8    58.1 2366.72    61.9 2365.56
    65.6 2363.69    67.3 2363.53    84.3 2364.79    91.5 2364.22   103.5 2362.21
   110.5 2362.26   115.6    2362   121.7 2362.24   129.2 2362.59     147 2366.63
   159.1 2367.97   179.7 2367.62   253.4 2370.04   265.5 2371.11   293.8 2371.93
   386.3 2372.57   405.7 2373.47   409.7  2374.1     425 2378.61   466.5 2400.01
#Mann= 5 ,-1 , 0
       0     .12       0   110.5    .045       0   121.7     .12       0
   303.3     .06       0  429.26      .1       0
Bank Sta=110.5,121.7
XS Rating Curve= 0 ,0
Exp/Cntr=0.3,0.1

Type RM Length L Ch R = 1 ,22622   ,267.6,267.5,266.3
XS GIS Cut Line= 2
2207070.64364595378670.5496085132207287.02325398379028.339180798
#Sta/Elev= 30
       0 2405.01      23 2392.69    26.8 2390.14    30.7 2388.52    34.2  2385.7
    38.3 2381.25    46.4 2373.77    53.7 2366.35    57.5 2361.71    59.6 2360.06
    63.1  2359.3    80.5 2360.03      87 2360.67    97.6 2363.23   107.4 2363.89
   134.8 2363.11   144.3 2360.95   154.7 2363.16     161 2363.47   170.6 2362.67
   177.8    2361   199.3 2364.12   218.1 2363.38   245.4 2364.62   275.1 2364.54
   283.7 2365.31   314.4 2364.96   356.6 2367.21   376.1 2372.63   418.1  2392.6
#Mann= 7 ,-1 , 0
       0      .1       0   56.33      .1       0    59.6    .045       0
    80.5      .1       0  129.15     .12       0  222.71     .06       0
  354.11      .1       0
#XS Ineff= 2 , 0
                          199.37         2364.84
Permanent Ineff=
       F       F
Bank Sta=59.6,80.5
XS Rating Curve= 0 ,0
Exp/Cntr=0.3,0.1

Type RM Length L Ch R = 1 ,22355   ,203.4,205.8,206.8
XS GIS Cut Line= 2
2206848.85864397378811.1091016172207049.69668741 379110.11457526
#Sta/Elev= 30
       0 2409.99     8.5 2405.05    16.4 2398.68      24 2393.69    35.3 2385.25
    44.1  2375.8      52 2364.18    58.8 2358.36    61.22357.376    68.9 2356.81
    78.4 2357.33    87.6 2357.98    95.5 2360.52    99.4 2361.06   119.2 2359.75
   127.1 2358.58     153 2360.69   194.3  2358.1   198.2  2358.7   202.2 2360.72
   206.1 2361.84   245.7 2361.34     251 2361.77   274.6 2361.59   281.2 2362.27
   285.2 2363.22     301 2369.14   335.4 2386.75   352.6 2396.81   360.2 2400.49
#Mann= 7 ,-1 , 0
       0      .1       0   16.24     .12       0    61.2    .045       0
    78.4     .12       0   90.88     .06       0   231.5      .1       0
  274.75      .1       0
#XS Ineff= 2 , 0
                          213.26         2361.83
Permanent Ineff=
       F       F
Bank Sta=61.2,78.4
XS Rating Curve= 0 ,0
Exp/Cntr=0.3,0.1

Type RM Length L Ch R = 1 ,22149   ,293.6,296.3,291.8
XS GIS Cut Line= 2
2206678.76904557378883.803775179 2206793.0844773379169.884483424
#Sta/Elev= 30
       0    2400     3.5 2397.04     9.7 2392.78    19.8 2386.51    31.8 2376.99
    35.3 2373.43    38.9 2370.43    49.5 2362.84    55.1 2359.47    63.6 2356.24
    77.7 2355.72    95.4 2356.18   105.6 2356.08   113.2 2357.16   127.2 2357.66
   155.5 2357.33   186.4 2358.34   194.3 2358.02     199 2356.64   204.9 2356.07
   214.2 2357.59   222.6 2356.81   236.7 2357.22   240.2 2357.79     254 2361.78
     265 2366.81   277.5 2368.88   292.4 2373.05   297.5 2374.83   308.1    2380
#Mann= 5 ,-1 , 0
       0      .1       0   19.95     .12       0    63.6    .045       0
    95.4     .12       0  200.12      .1       0
Bank Sta=63.6,95.4
XS Rating Curve= 0 ,0
Exp/Cntr=0.3,0.1

Type RM Length L Ch R = 1 ,21853   ,185.5,192,192.1
XS GIS Cut Line= 2
 2206409.2269773  378967.84688992206540.46031063 379295.60746605
#Sta/Elev= 30
       0    2420      12 2411.13    33.2 2393.46    40.2 2388.78    50.8 2380.15
      59 2371.87    66.6 2362.84    75.6 2355.57    82.6  2353.5   100.3 2354.83
   107.4 2354.06   121.5 2354.89   132.4 2353.73   142.7 2353.26   153.3 2353.67
     160 2354.21   163.9 2355.85   167.5 2356.15   185.1 2354.94   240.7  2355.8
   266.4 2354.19   273.5 2354.62     277 2356.23   291.1 2369.16   294.7 2371.49
   301.7 2373.56   308.8 2374.23   316.4 2376.55   333.6 2378.95   353.1    2385
#Mann= 5 ,-1 , 0
       0      .1       0   25.66      .1       0   132.4    .045       0
   153.3      .1       0  155.57      .1       0
Bank Sta=132.4,153.3
XS Rating Curve= 0 ,0
Exp/Cntr=0.3,0.1

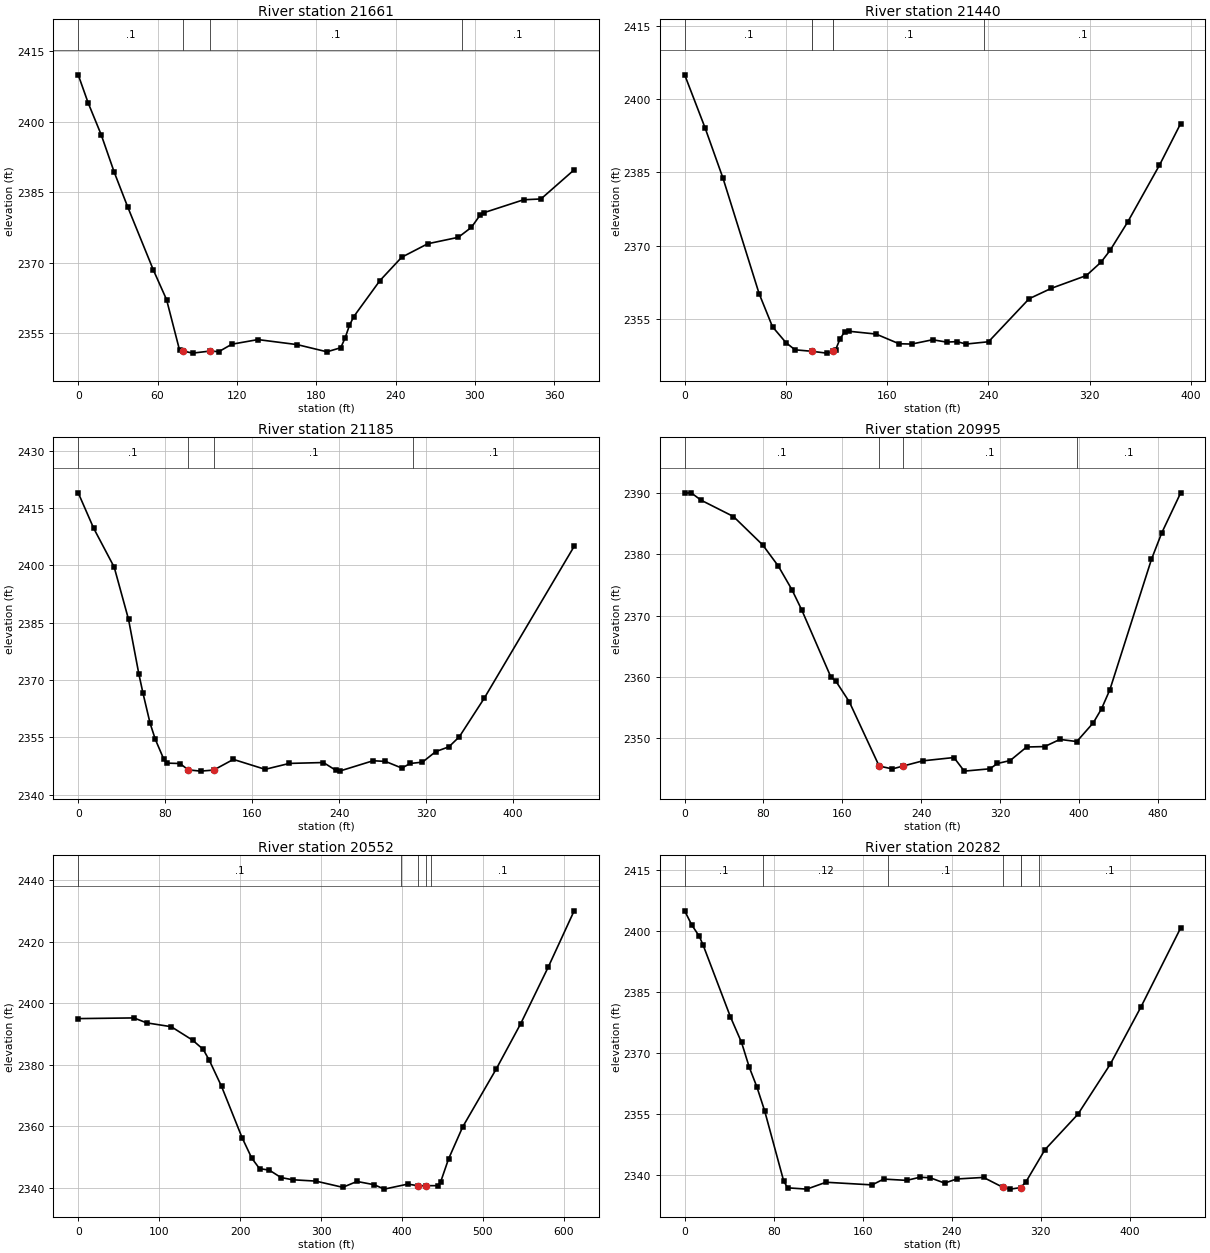
Type RM Length L Ch R = 1 ,21661   ,222.1,220.5,215.5
XS GIS Cut Line= 2
2206284.55531063379017.3934471162206316.28358202379391.071747235
#Sta/Elev= 30
       0 2409.99     7.5 2404.03    17.4 2397.23    27.3 2389.22    37.3 2381.97
    56.9 2368.41    66.8 2362.17    76.7 2351.34    79.42351.225    86.5 2350.78
    99.7 2351.22   106.3 2351.09   116.2 2352.68   135.9 2353.66   165.6 2352.59
   188.1 2351.06   198.5 2351.93   201.8 2353.99   205.1  2356.7   208.4 2358.57
   228.1  2366.2   244.6 2371.18   264.3 2374.05   287.4 2375.42   297.3 2377.54
   303.9 2380.15   307.1 2380.69   336.8 2383.41   349.9 2383.58     375 2389.78
#Mann= 4 ,-1 , 0
       0      .1       0    79.4    .045       0    99.7      .1       0
  290.07      .1       0
Bank Sta=79.4,99.7
XS Rating Curve= 0 ,0
Exp/Cntr=0.3,0.1

Type RM Length L Ch R = 1 ,21440   ,256.6,255.1,253
XS GIS Cut Line= 2
 2206054.8969773379092.0323647032206205.81531064379453.690741084
#Sta/Elev= 30
       0 2405.01    16.1 2394.15    30.3 2383.81    58.8 2360.18    69.4 2353.37
    80.1  2350.1    87.2 2348.65   100.72348.341   112.1 2347.97   116.92348.311
   119.2 2348.62   122.8 2350.91   126.3 2352.29   129.9 2352.45   151.2 2351.88
   169.4 2349.89   179.4 2349.83   195.9 2350.71     207 2350.23   215.2 2350.33
   222.3 2349.83   240.1  2350.3   272.2 2359.12   289.8 2361.26   317.4 2363.87
     329 2366.61   336.1 2369.01     350 2374.81   375.2  2386.5   391.9 2395.01
#Mann= 6 ,-1 , 0
       0      .1       0  100.65      .1       0   100.7    .045       0
   116.9      .1       0  116.91      .1       0  236.57      .1       0
Bank Sta=100.7,116.9
XS Rating Curve= 0 ,0
Exp/Cntr=0.3,0.1

Type RM Length L Ch R = 1 ,21185   ,191.4,190,187.6
XS GIS Cut Line= 2
 2205798.9919773 379163.44486042 2206025.3694773379559.367957093
#Sta/Elev= 30
       0    2419    14.2 2409.74    33.1 2399.54    46.3 2385.85    55.8 2371.54
    59.6 2366.52    66.1 2358.69    70.9 2354.48    78.5 2349.41    81.2 2348.26
    93.6 2348.15   101.2 2346.49   112.5 2346.16   124.5 2346.43   142.7 2349.23
   171.9 2346.63   194.2 2348.18   225.5 2348.41   237.2 2346.33     241 2346.22
   271.2 2348.88   282.6  2348.7   297.7 2346.95   305.2 2348.16   316.6 2348.51
   328.8 2351.27   340.9 2352.52   350.5 2355.15   373.3 2365.19   456.1 2404.99
#Mann= 4 ,-1 , 0
       0      .1       0   101.2    .045       0   124.5      .1       0
  308.21      .1       0
Bank Sta=101.2,124.5
XS Rating Curve= 0 ,0
Exp/Cntr=0.3,0.1

Type RM Length L Ch R = 1 ,20995   ,442.1,442.8,436.5
XS GIS Cut Line= 3
2205644.99691778379172.517108511 2205661.1969773379319.881984096
2205884.84425056379595.744608515
#Sta/Elev= 30
       0 2389.99     6.6 2390.04    16.5 2388.85    49.5 2386.17    79.2 2381.53
      95 2378.09   108.9 2374.21   118.8 2370.92   148.3 2359.99   153.5 2359.27
   167.1 2355.91   197.4 2345.42   210.8 2344.95   221.2  2345.4   241.7 2346.27
   273.3 2346.81   283.8 2344.59   309.8 2344.97   317.5 2345.84   330.4 2346.32
   347.1 2348.53   365.4  2348.6   380.9 2349.77     398 2349.42   414.7 2352.47
   423.1 2354.76   431.6 2357.89   473.8 2379.18   484.3 2383.52   503.4 2390.01
#Mann= 4 ,-1 , 0
       0      .1       0   197.4    .045       0   221.2      .1       0
  398.01      .1       0
Bank Sta=197.4,221.2
XS Rating Curve= 0 ,0
Exp/Cntr=0.3,0.1

Type RM Length L Ch R = 1 ,20552   ,268.4,270.8,273
XS GIS Cut Line= 3
 2205385.6069773379327.0627658232205399.00810246379480.915441842
2205625.10781063379879.537810439
#Sta/Elev= 30
       0    2395    68.8 2395.22    84.5 2393.62   114.9 2392.37   141.3    2388
   154.4 2385.01     162 2381.44   177.1 2372.97   202.4 2356.37   214.4 2349.68
     224 2346.28   236.1 2345.79   250.5 2343.38   264.9 2342.66   293.5 2342.23
   326.8 2340.21   344.4 2342.11   365.7 2341.05   378.1 2339.62   407.1 2341.25
   419.32340.747   429.8 2340.75   444.9 2340.74   447.9 2342.07   457.5 2349.41
     475 2359.83   516.5 2378.66   546.7 2393.37   580.7 2411.74   612.7    2430
#Mann= 5 ,-1 , 0
       0      .1       0  398.19      .1       0   419.3    .045       0
   429.8      .1       0  435.32      .1       0
Bank Sta=419.3,429.8
XS Rating Curve= 0 ,0
Exp/Cntr=0.3,0.1

Type RM Length L Ch R = 1 ,20282   ,243.4,246.4,249.8
XS GIS Cut Line= 2
2205231.40781063379576.7367130792205369.67865416380000.309041692
#Sta/Elev= 30
       0 2404.99     6.2 2401.59    13.1 2398.73    16.5 2396.62    41.1 2378.92
    51.1 2372.63      58 2366.56    64.9 2361.67    71.8 2355.86      89 2338.51
    92.5 2336.88   109.7 2336.56     127 2338.25   168.4  2337.6   178.8 2339.03
   199.5 2338.71   211.4 2339.49   220.6 2339.35   233.6 2338.04   244.3 2339.05
   268.5 2339.44   285.8 2337.02   292.6 2336.56   301.82336.932   306.5 2338.29
   323.7 2346.26   353.3 2354.97   382.4 2367.28     410 2381.37   445.6 2400.76
#Mann= 7 ,-1 , 0
       0      .1       0    70.5     .12       0  182.94      .1       0
   285.8    .045       0   301.8      .1       0  301.81      .1       0
  318.43      .1       0
Bank Sta=285.8,301.8
XS Rating Curve= 0 ,0
Exp/Cntr=0.3,0.1