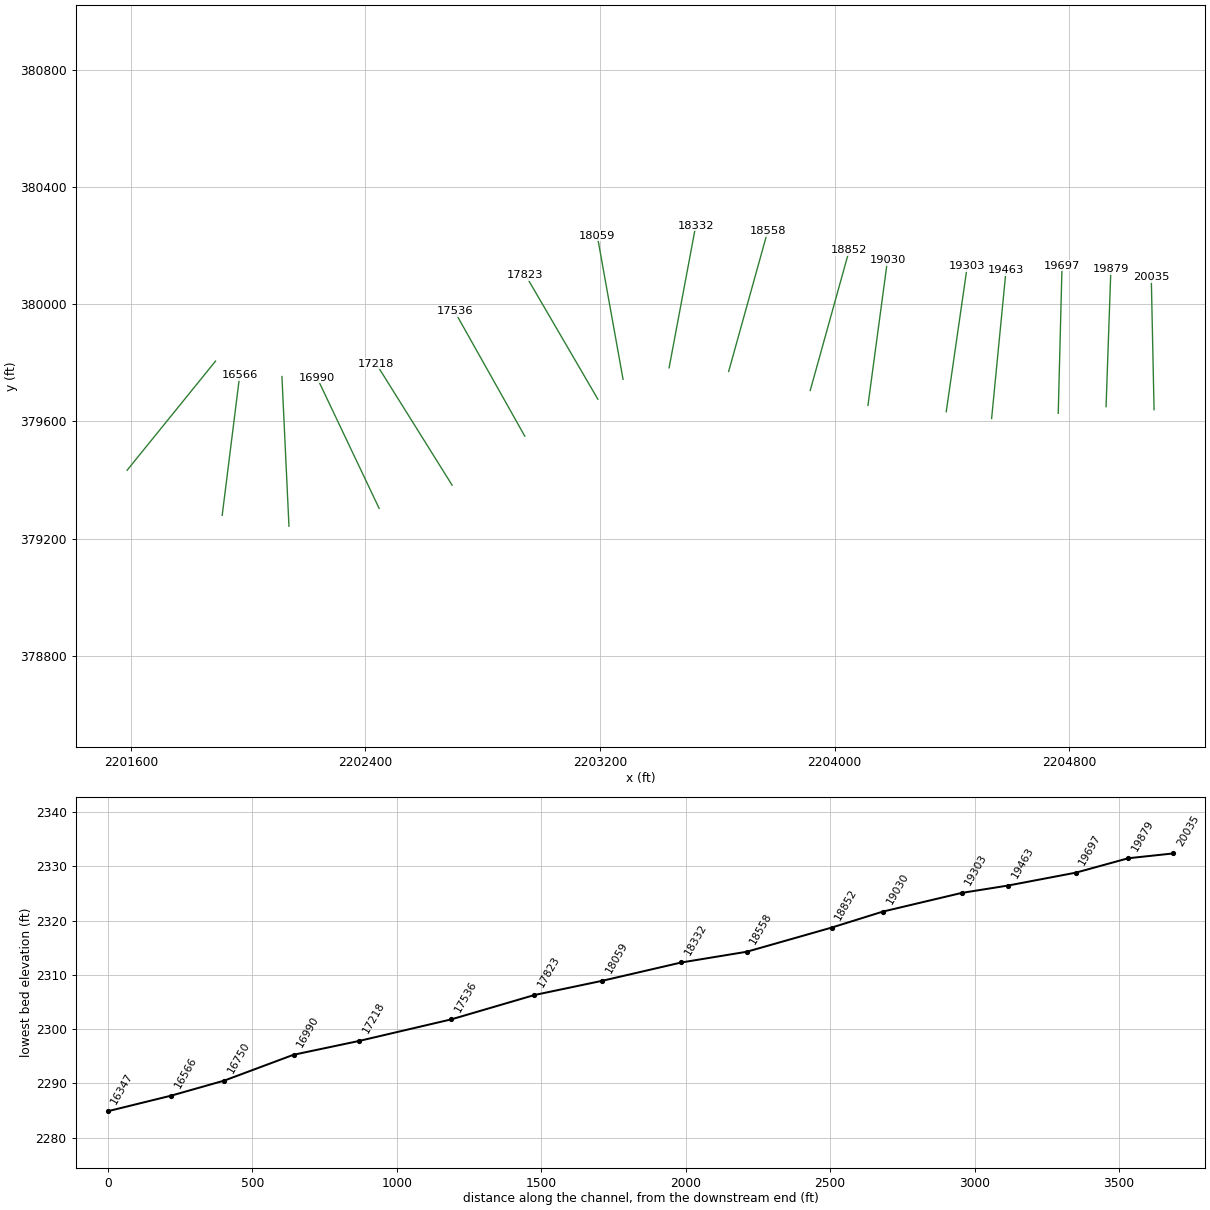
HEC-RAS study SPICERN.prj: SPICERN

--- SPICERN.g01 (geometry) --- (continued)

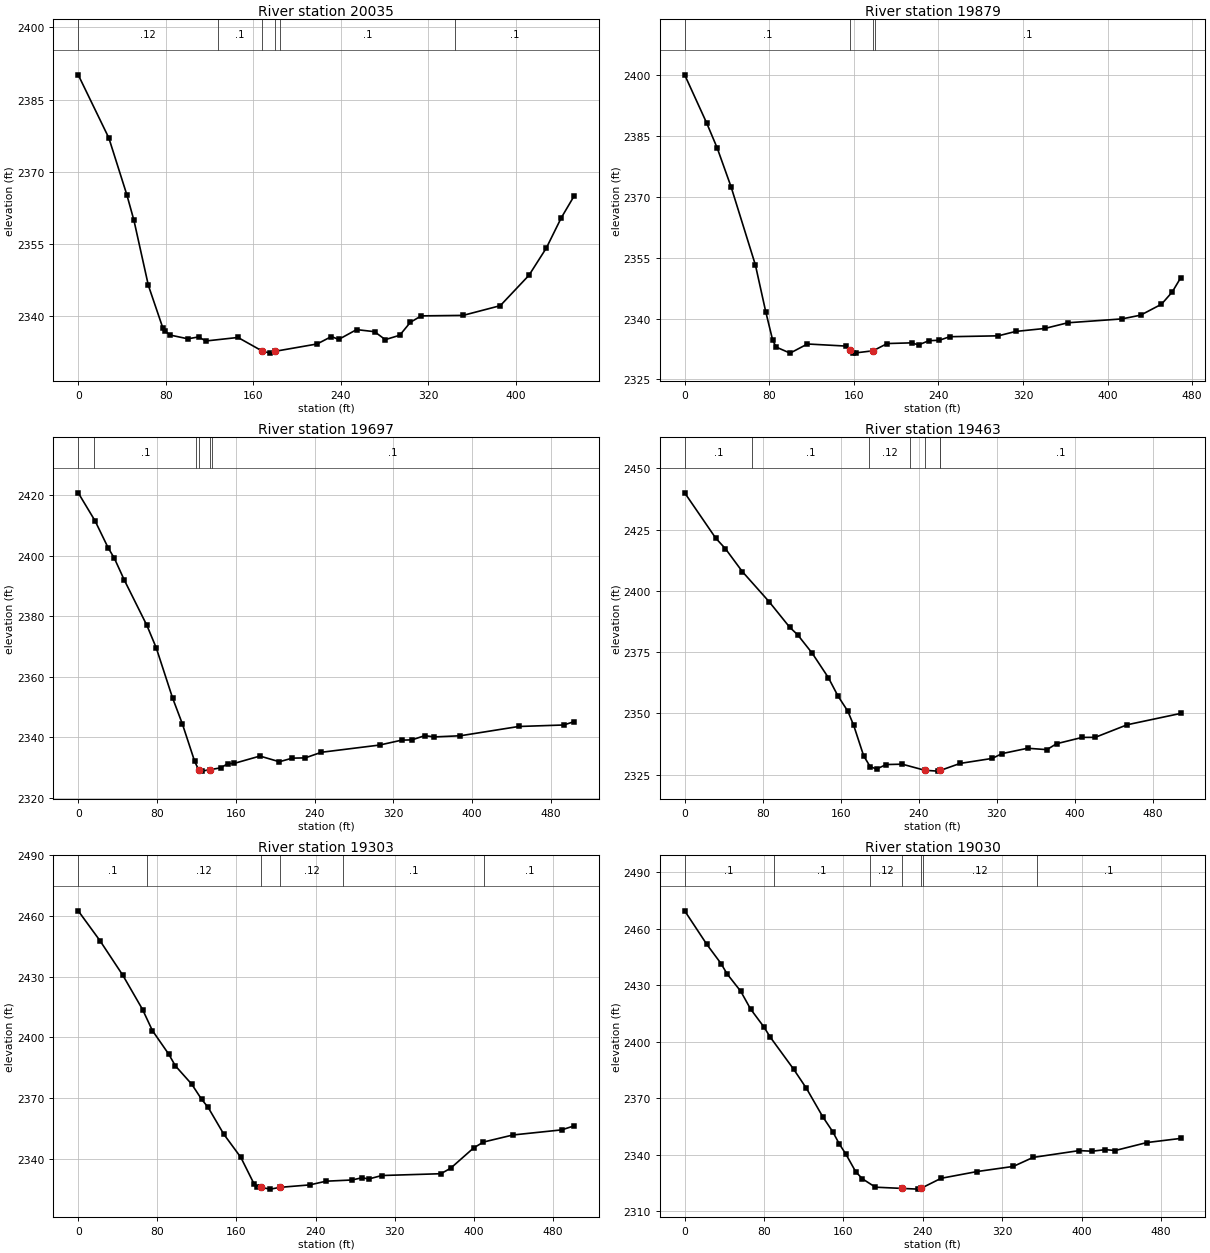
Type RM Length L Ch R = 1 ,20035   ,156.5,156.2,155.8
XS GIS Cut Line= 2
2205090.05546044379639.964015443 2205080.4894773380093.078106242
#Sta/Elev= 30
       0 2390.13      28 2377.02    44.4 2365.26    50.9 2359.95    64.1 2346.44
    77.2 2337.69    79.1    2337    83.8 2336.14   100.2 2335.35     110 2335.74
   116.6  2334.9     146 2335.63   168.42332.781   175.6 2332.38   179.7 2332.75
   218.3 2334.28   231.4 2335.82     238 2335.22   254.4 2337.26   270.8 2336.83
   280.6 2335.18   293.8 2336.09   303.6 2338.79   313.5 2340.11   351.7 2340.21
   385.7 2342.23   411.9 2348.53   427.8  2354.2   441.4 2360.45   453.2    2365
#Mann= 6 ,-1 , 0
       0     .12       0   127.6      .1       0   168.4    .045       0
   179.7      .1       0  184.66      .1       0  344.65      .1       0
Bank Sta=168.4,179.7
XS Rating Curve= 0 ,0
Exp/Cntr=0.3,0.1

Type RM Length L Ch R = 1 ,19879   ,176.9,181.8,181.6
XS GIS Cut Line= 2
2204926.29031064379650.307674302 2204942.6944773 380119.13900674
#Sta/Elev= 30
       0    2400    20.9 2388.08    30.8 2381.96    43.9 2372.42    66.9 2353.18
    76.7 2341.65    83.3  2334.6    86.6 2332.97    99.7 2331.49   116.1 2333.74
   152.2 2333.23   156.6 2332.19   158.8 2331.61   162.1 2331.56   178.2 2332.07
   191.6 2333.85   214.6 2334.02   221.2 2333.51     231 2334.55   240.9 2334.66
   250.7 2335.53   296.7 2335.75   313.1 2336.83   340.6 2337.56   362.3 2338.96
   413.5 2339.91   431.3 2340.84     451 2343.53   461.1 2346.52   469.1    2350
#Mann= 4 ,-1 , 0
       0      .1       0   156.6    .045       0   178.2      .1       0
   180.2      .1       0
Bank Sta=156.6,178.2
XS Rating Curve= 0 ,0
Exp/Cntr=0.3,0.1

Type RM Length L Ch R = 1 ,19697   ,233.4,234.1,234.2
XS GIS Cut Line= 2
2204763.13892715379627.8159635232204776.10633897380131.154912644
#Sta/Elev= 30
       0 2420.81    17.1 2411.55    30.3  2402.7    36.8 2399.11    46.7 2392.04
    69.7 2377.01    79.2 2369.59    95.8 2353.01   105.8 2344.39   118.2 2332.07
   122.2 2329.32   125.5 2328.83   134.2 2329.33   145.1 2329.95   151.7 2331.31
   158.3 2331.38   184.5 2333.81   204.2 2331.93   217.3 2333.12   230.5 2333.21
   246.9 2335.06     306 2337.45   328.4 2339.07   338.8 2339.16   351.8 2340.55
   361.7 2340.14     388 2340.52   447.1 2343.58     493 2344.08   503.5 2345.19
#Mann= 6 ,-1 , 0
       0      .1       0   16.36      .1       0  119.98      .1       0
   122.2    .045       0   134.2      .1       0  135.99      .1       0
Bank Sta=122.2,134.2
XS Rating Curve= 0 ,0
Exp/Cntr=0.3,0.1

Type RM Length L Ch R = 1 ,19463   ,160.5,160.5,158
XS GIS Cut Line= 2
2204535.87114397379609.9250679562204585.08364397380116.036431777
#Sta/Elev= 30
       0 2440.01    31.9 2421.48    41.8  2417.2    59.1 2407.88    86.5 2395.62
   107.7 2385.15   115.7 2382.15   130.8 2374.55   147.3 2364.62   157.2 2357.09
   167.3  2350.9   173.3 2345.13   183.5 2332.72   190.1 2328.34   196.7  2327.3
   206.6 2329.15   223.1 2329.29   246.2 2326.81   259.3 2326.46   262.2 2326.75
   282.4 2329.61   315.4 2331.65   325.3  2333.6   351.6 2335.79   371.4 2335.23
   381.3 2337.64   407.7 2340.23   420.9 2340.24   453.8 2345.39   508.5    2350
#Mann= 7 ,-1 , 0
       0      .1       0   68.96      .1       0  189.21     .12       0
  231.41      .1       0   246.2    .045       0   262.2      .1       0
  262.23      .1       0
Bank Sta=246.2,262.2
XS Rating Curve= 0 ,0
Exp/Cntr=0.3,0.1

Type RM Length L Ch R = 1 ,19303   ,272,272.8,272.2
XS GIS Cut Line= 2
2204381.03838633379633.0234378312204452.75871404380129.475567425
#Sta/Elev= 30
       0 2462.57      22 2447.83    45.2 2430.68    65.1 2413.82      75 2403.44
    91.6 2391.74    98.2 2386.03   114.8 2376.94   124.8 2369.48   131.4 2365.47
   147.2 2352.26   164.5 2340.76   177.8 2327.72   181.1 2326.33   184.82325.928
   194.4  2325.1   204.3 2325.99   234.2 2327.19   250.7 2329.02   276.8 2329.61
   287.2 2330.73   293.8 2330.11   307.1 2331.82   366.8 2332.71   376.7 2335.43
   399.9 2345.44   409.8 2348.35   439.7 2351.85     489 2354.37   501.6 2356.35
#Mann= 6 ,-1 , 0
       0      .1       0   69.85     .12       0   184.8    .045       0
   204.3     .12       0  268.24      .1       0  410.85      .1       0
Bank Sta=184.8,204.3
XS Rating Curve= 0 ,0
Exp/Cntr=0.3,0.1

Type RM Length L Ch R = 1 ,19030   ,179.9,177.9,175.7
XS GIS Cut Line= 2
2204114.03625756379654.5910580942204180.65668843380149.937057955
#Sta/Elev= 30
       0 2469.47    22.3 2451.66    36.6 2441.49    42.7    2436    56.5 2426.74
    66.4 2417.32    79.7 2407.89    86.3 2402.34   109.8 2385.36   122.7 2375.18
   139.2 2360.06   149.2 2352.17   155.8 2345.66   162.4  2340.3   172.3 2330.96
     179 2327.18   192.2 2322.69   218.7 2322.05   235.2 2321.66   238.2 2322.09
   258.4 2327.41   294.8 2331.01   331.2 2333.72   351.1  2338.5   397.5 2342.12
   410.7  2341.8   423.9 2342.63   433.9 2342.17   465.8  2346.4   499.8 2348.59
#Mann= 7 ,-1 , 0
       0      .1       0   89.63      .1       0  187.17     .12       0
   218.7    .045       0   238.2     .12       0  239.91     .12       0
  355.34      .1       0
Bank Sta=218.7,238.2
XS Rating Curve= 0 ,0
Exp/Cntr=0.3,0.1

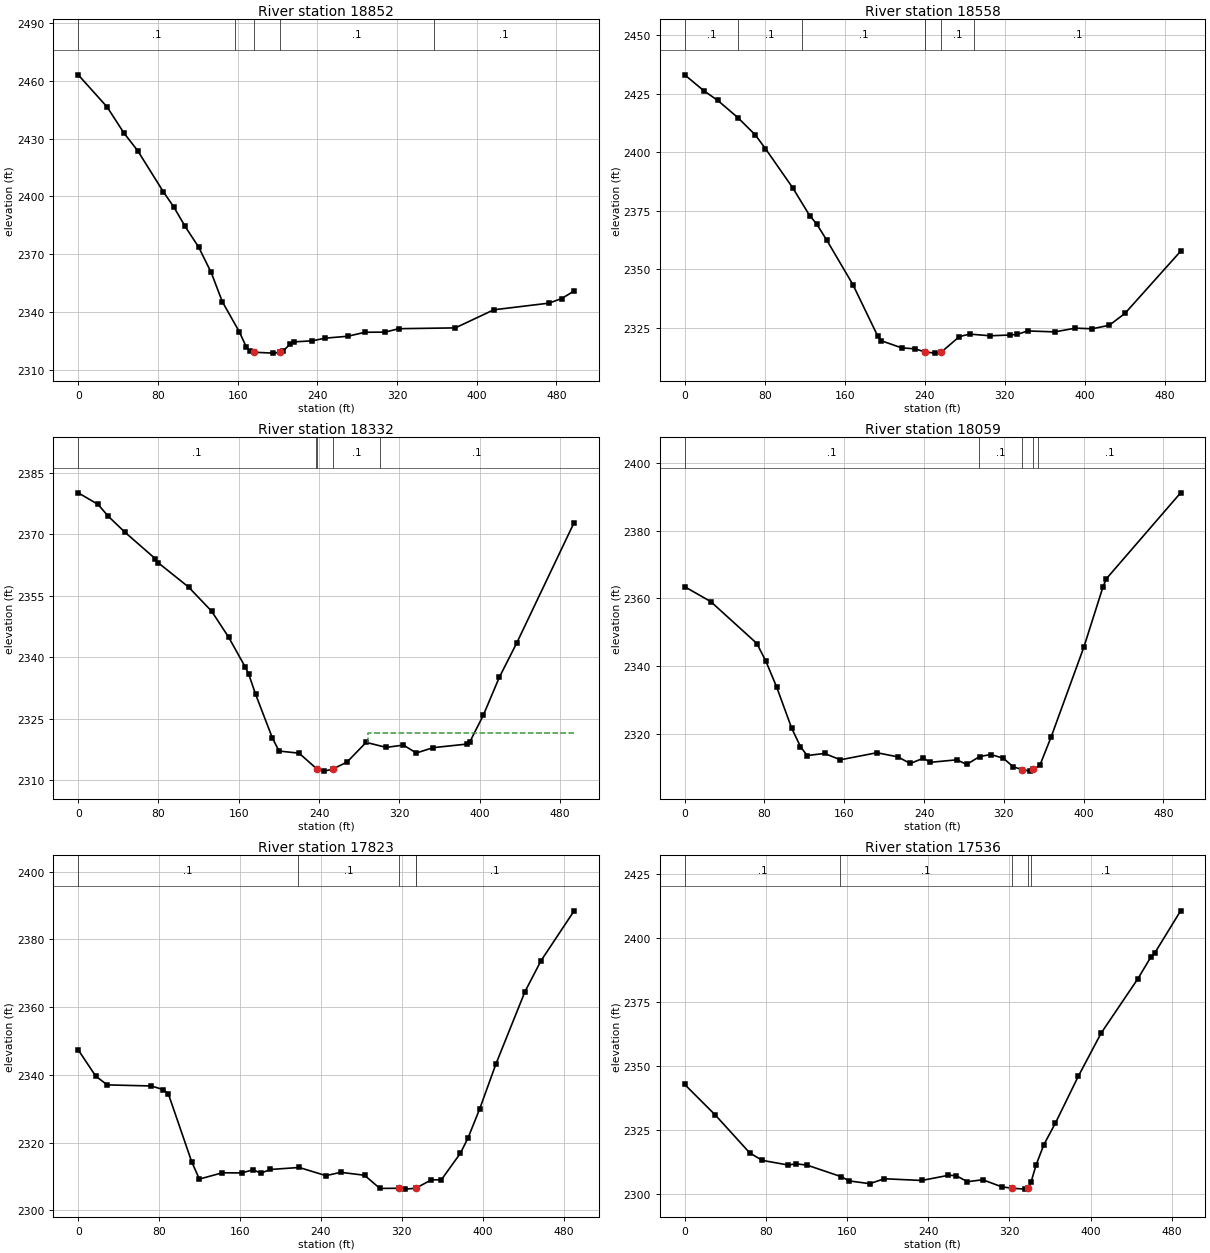
Type RM Length L Ch R = 1 ,18852   ,294.1,293.6,292.6
XS GIS Cut Line= 2
2203917.09958004379705.6319232372204050.50787834 380185.33234911
#Sta/Elev= 30
       0 2463.04      29 2446.36      46 2432.79    59.6 2423.77    85.5 2402.36
    96.2  2394.3   107.3 2384.42   120.9  2373.7   133.5 2360.52   144.7 2345.35
   161.8  2329.7   168.6 2322.06     172 2319.93   176.1 2319.17   195.8  2318.7
   202.8 2319.11     206 2319.91   212.9 2323.49   216.3 2324.53   234.8 2325.07
   248.1 2326.47   270.7 2327.46     288 2329.52   308.2  2329.6   321.8 2331.37
   378.6 2331.79   417.2 2341.17   472.7 2344.63   485.3 2347.01   497.9 2350.92
#Mann= 5 ,-1 , 0
       0      .1       0  157.57      .1       0   176.1    .045       0
   202.8      .1       0  357.38      .1       0
Bank Sta=176.1,202.8
XS Rating Curve= 0 ,0
Exp/Cntr=0.3,0.1

Type RM Length L Ch R = 1 ,18558   ,225.6,226.6,226.9
XS GIS Cut Line= 2
2203638.88266631379770.5525554882203771.81639574380248.412835897
#Sta/Elev= 30
       0 2433.15    19.5 2426.24    33.1 2422.21    53.5 2414.74    70.6 2407.48
    80.8  2401.6     108 2384.91     125 2373.02   131.9 2369.49   142.1 2362.52
   168.2 2343.55   193.1 2321.52   196.6 2319.54     217  2316.5   230.6 2316.07
   240.72314.704   250.8 2314.25   256.72314.695   274.7 2321.31   285.1 2322.38
   305.5 2321.66   325.4 2321.99   332.8 2322.29     343 2323.73   370.2 2323.32
   390.7 2324.92   407.7 2324.65   424.7 2326.17   440.3 2331.21     496 2357.78
#Mann= 7 ,-1 , 0
       0      .1       0    53.4      .1       0  117.65      .1       0
  240.68      .1       0   240.7    .045       0   256.7      .1       0
  289.28      .1       0
Bank Sta=240.7,256.7
XS Rating Curve= 0 ,0
Exp/Cntr=0.3,0.1

Type RM Length L Ch R = 1 ,18332   ,270.1,273.2,273.8
XS GIS Cut Line= 2
2203435.71673971379782.9472024412203526.70111356380268.705658464
#Sta/Elev= 30
       0 2380.14    19.8 2377.31    29.8 2374.46    46.5 2370.54    76.7  2364.1
    79.9 2363.05     110 2357.15   132.9 2351.28   149.8 2344.97   166.6 2337.59
     170 2335.84   176.7 2331.06   193.4  2320.4   200.1 2317.17   220.1 2316.65
   237.5 2312.87   245.3 2312.27   253.52312.771   267.8 2314.46   286.9 2319.28
   306.9 2318.06   324.1 2318.62   336.9 2316.69   353.6 2317.99     387 2318.86
   390.3 2319.43   403.7 2325.91   419.6 2335.14   437.1 2343.58   494.2  2372.9
#Mann= 5 ,-1 , 0
       0      .1       0  237.01      .1       0   237.5    .045       0
   253.5      .1       0  301.07      .1       0
#XS Ineff= 2 , 0
                          289.19         2321.57
Permanent Ineff=
       F       F
Bank Sta=237.5,253.5
XS Rating Curve= 0 ,0
Exp/Cntr=0.3,0.1

Type RM Length L Ch R = 1 ,18059   ,232,235.3,235.5
XS GIS Cut Line= 2
2203278.59555999379743.940389451 2203190.7294773380233.323561503
#Sta/Elev= 30
       0 2363.41    26.1 2359.02    72.4 2346.62    81.5 2341.33    92.2 2333.77
   107.3 2321.57   116.1 2316.13   122.8  2313.5   140.2 2314.13   156.1 2312.25
   192.8 2314.34   213.7 2313.11   226.1 2311.16   239.4 2312.73   246.1  2311.5
   272.8 2312.24   282.8 2310.88   295.6  2313.2   306.9  2313.8   319.4 2312.74
   329.4 2310.17   338.52309.347   346.1  2308.9   349.4  2309.4   356.1 2310.62
   367.3 2318.93   400.2 2345.56   419.4 2363.37   422.7 2365.74   497.2 2391.16
#Mann= 5 ,-1 , 0
       0      .1       0   295.2      .1       0   338.5    .045       0
   349.4      .1       0  354.55      .1       0
Bank Sta=338.5,349.4
XS Rating Curve= 0 ,0
Exp/Cntr=0.3,0.1

Type RM Length L Ch R = 1 ,17823   ,286.6,287.3,286.7
XS GIS Cut Line= 2
2203192.62579266379675.9297016592202945.81735842380099.702570118
#Sta/Elev= 30
       0  2347.4    17.3 2339.64    28.7 2337.05    72.3 2336.73    84.3 2335.64
    89.1 2334.42   112.2 2314.36   119.8 2309.24   142.6  2311.1   161.6 2311.05
     173 2311.98   180.6 2310.97   189.9 2312.07   218.5 2312.66     245 2310.25
   259.5 2311.23   283.1 2310.37   298.3 2306.48   317.3 2306.52   323.2 2306.27
   333.8 2306.53   349.3 2309.03     359    2309     378  2316.9   385.6  2321.5
     397 2329.97     413 2343.19   441.8 2364.61   457.7 2373.75   490.4 2388.45
#Mann= 5 ,-1 , 0
       0      .1       0  217.49      .1       0   317.3    .045       0
   333.8      .1       0  334.29      .1       0
Bank Sta=317.3,333.8
XS Rating Curve= 0 ,0
Exp/Cntr=0.3,0.1

Type RM Length L Ch R = 1 ,17536   ,317.5,318.3,318.2
XS GIS Cut Line= 2
 2202943.3596136379549.6624617652202704.12561422379975.693811588
#Sta/Elev= 30
       0 2342.71    30.3  2330.7    64.1 2315.94    76.3 2313.04   101.8 2311.22
     110 2311.67   120.6 2311.17   154.4 2306.63     162 2305.01   182.3 2303.92
   196.7 2305.85   233.5 2305.17   259.8 2307.19   267.3 2307.09   278.6 2304.69
   293.7 2305.45   312.4 2302.69     322 2302.16   335.1 2301.79   338.5  2302.2
   341.3 2304.63   346.3 2311.32   353.9 2319.21   365.2 2327.56   387.7 2345.82
   410.3 2362.76   446.3  2383.9   459.2 2392.44     463 2393.99   488.6 2410.56
#Mann= 5 ,-1 , 0
       0      .1       0  153.03      .1       0     322    .045       0
   338.5      .1       0  340.97      .1       0
Bank Sta=322,338.5
XS Rating Curve= 0 ,0
Exp/Cntr=0.3,0.1

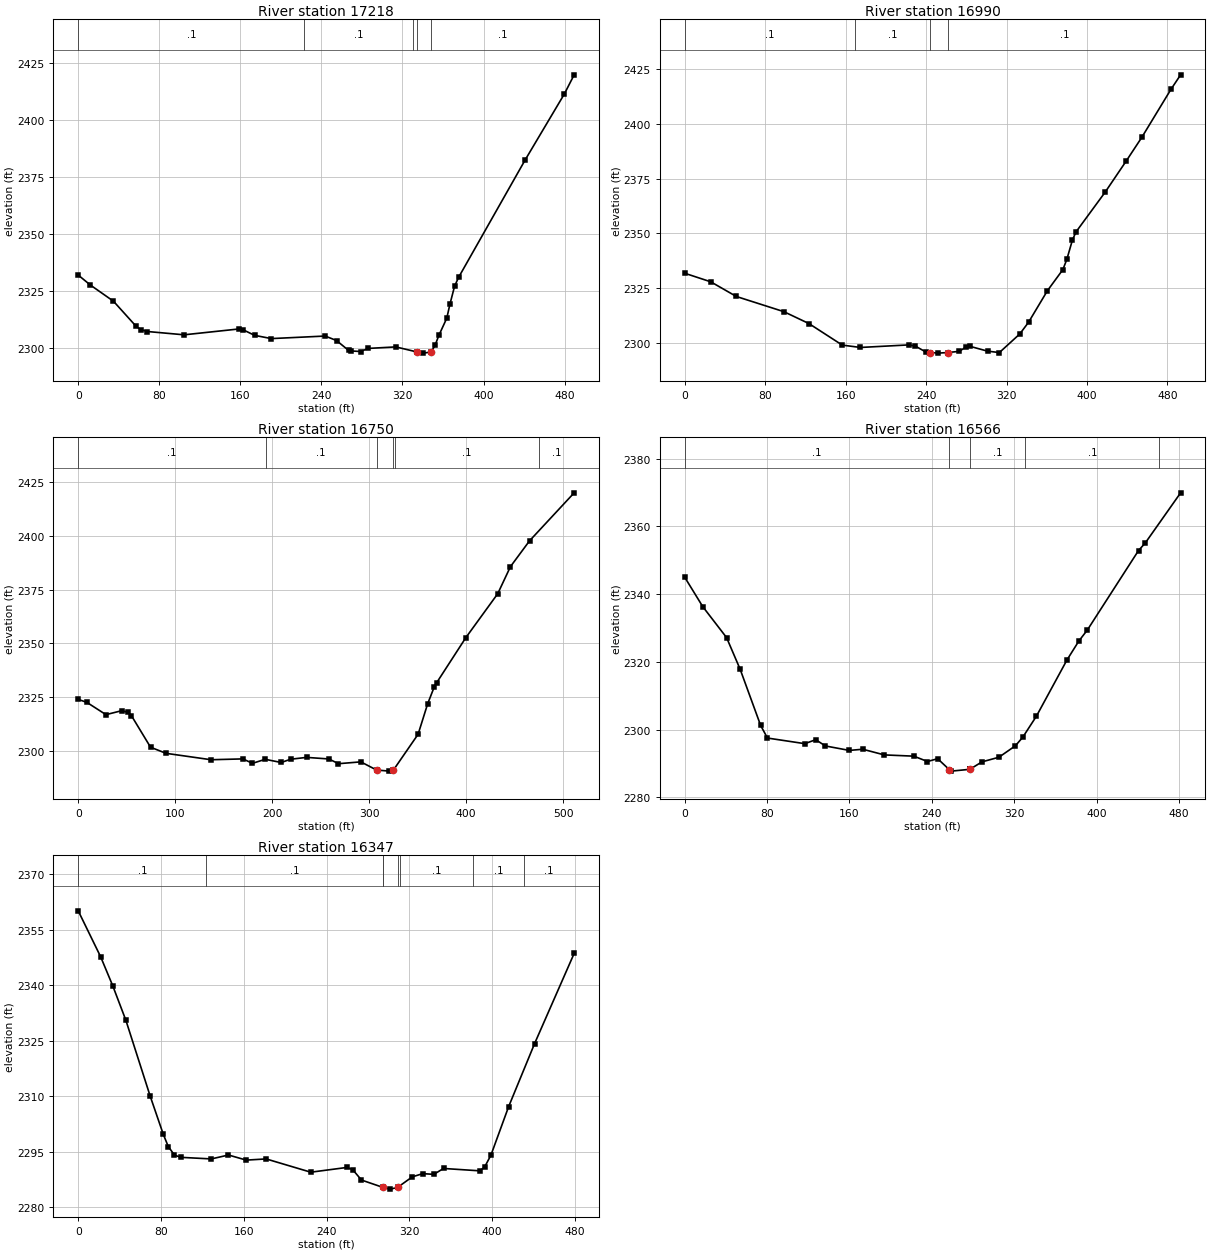
Type RM Length L Ch R = 1 ,17218   ,229.4,227.9,226.5
XS GIS Cut Line= 2
2202695.44523736379382.4670041012202436.13781064379797.548181208
#Sta/Elev= 30
       0 2332.09      12 2327.71    34.8  2320.6    57.2 2309.56    61.9 2308.11
    68.3 2307.31   104.5 2305.86   158.6 2308.43   162.5 2308.11   174.1 2305.62
   190.6  2304.2   243.7 2305.32   254.9 2303.35   266.9 2298.98   269.2 2298.78
   278.6 2298.53   286.3 2299.89   313.4 2300.55   334.6  2298.3   340.4 2297.82
   348.2 2298.29   352.1 2301.21   355.9 2305.61   363.7 2313.16   366.8 2319.26
   371.4 2327.19   375.3 2331.02     441 2382.59   479.7 2411.57   489.4 2419.99
#Mann= 5 ,-1 , 0
       0      .1       0  223.23      .1       0  330.43      .1       0
   334.6    .045       0   348.2      .1       0
Bank Sta=334.6,348.2
XS Rating Curve= 0 ,0
Exp/Cntr=0.3,0.1

Type RM Length L Ch R = 1 ,16990   ,241.2,239.7,234.1
XS GIS Cut Line= 2
2202446.46699859379303.2814978472202235.00738778379748.691165126
#Sta/Elev= 30
       0 2331.75    25.9 2327.84    51.4 2321.13    98.6  2314.2   123.5 2308.77
   156.7 2298.92   174.8 2297.85     223 2299.02   229.3 2298.48   239.6 2295.82
     2442295.532   251.9 2295.26     262 2295.54   272.9 2296.07   280.2 2298.19
   283.8 2298.34   301.2 2296.16   312.9 2295.52   333.2 2304.02   341.9 2309.36
   360.7  2323.8     376 2333.39     380 2338.12   385.5  2346.9   389.1 2350.63
   418.2 2368.87   439.1 2383.07   454.5 2393.81   483.5 2415.75   493.1 2422.37
#Mann= 4 ,-1 , 0
       0      .1       0  169.19      .1       0     244    .045       0
     262      .1       0
Bank Sta=244,262
XS Rating Curve= 0 ,0
Exp/Cntr=0.3,0.1

Type RM Length L Ch R = 1 ,16750   ,184.8,184.2,181.2
XS GIS Cut Line= 2
  2202138.931854379242.3669973832202114.98292136379753.224608516
#Sta/Elev= 30
       0 2323.88     8.9  2322.5    28.6 2316.78      45 2318.64    51.6 2317.79
    54.9 2316.29    74.6 2301.62    90.6 2298.78     137  2295.8   169.8 2296.19
   179.7 2294.13   192.8    2296   209.3 2294.52   219.1 2296.04   235.5 2296.89
   258.5 2296.16   268.4 2293.96   291.4 2294.81   307.7 2291.01   320.9  2290.5
     325 2290.98   350.5 2307.67   360.3 2321.78   366.9 2329.42   369.7 2331.69
   399.7 2352.61   432.6 2373.06   445.7 2385.65   465.4 2397.67   511.4    2420
#Mann= 6 ,-1 , 0
       0      .1       0  193.33      .1       0   307.7    .045       0
     325      .1       0  327.15      .1       0  474.69      .1       0
Bank Sta=307.7,325
XS Rating Curve= 0 ,0
Exp/Cntr=0.3,0.1

Type RM Length L Ch R = 1 ,16566   ,223.2,219.1,211.8
XS GIS Cut Line= 2
 2201911.2044773379279.7687746442201971.00378016379757.701407581
#Sta/Elev= 30
       0 2345.01    17.6 2336.29    40.7 2327.16    53.9 2317.79    73.8  2301.2
    80.4 2297.49   116.7 2295.83   127.3 2297.01   136.6 2295.16   159.9 2293.84
     173 2294.18   193.9 2292.51   222.6 2292.14   235.8 2290.56   245.7 2291.39
   256.92288.199   258.9 2287.72   277.1 2288.26   277.1 2288.27   288.7 2290.45
   305.2 2291.82   321.2  2295.2   328.4 2297.74   341.6 2303.93   371.3 2320.55
   382.9 2326.17   391.2 2329.44   440.8 2352.87   447.4 2355.12   481.7 2369.92
#Mann= 5 ,-1 , 0
       0      .1       0   256.9    .045       0   277.1      .1       0
  331.02      .1       0  460.99      .1       0
Bank Sta=256.9,277.1
XS Rating Curve= 0 ,0
Exp/Cntr=0.3,0.1

Type RM Length L Ch R = 1 ,16347   ,209.7,206.9,204.2
XS GIS Cut Line= 2
2201586.93045602379433.436065339 2201888.4655482379805.880257187
#Sta/Elev= 30
       0 2360.14    21.7 2347.69    33.4 2339.84    46.1 2330.49    69.5 2310.04
    82.2 2299.68      87 2296.38      93 2294.06    99.1 2293.45   128.6 2293.02
   145.2 2294.08   162.4  2292.7   181.6 2293.02   224.7 2289.43   259.5 2290.71
   265.1 2290.16   273.7 2287.31   294.52285.315   301.6 2284.85   308.6 2285.32
   322.8 2288.17   332.9 2289.04   343.6 2288.85     353 2290.44     388  2289.8
   392.6 2290.78   398.8 2294.05   415.9 2307.17     441 2324.24   479.2 2348.62
#Mann= 8 ,-1 , 0
       0      .1       0  123.79      .1       0  294.48      .1       0
   294.5    .045       0   308.6      .1       0  310.48      .1       0
  381.63      .1       0  431.03      .1       0
Bank Sta=294.5,308.6
XS Rating Curve= 0 ,0
Exp/Cntr=0.3,0.1