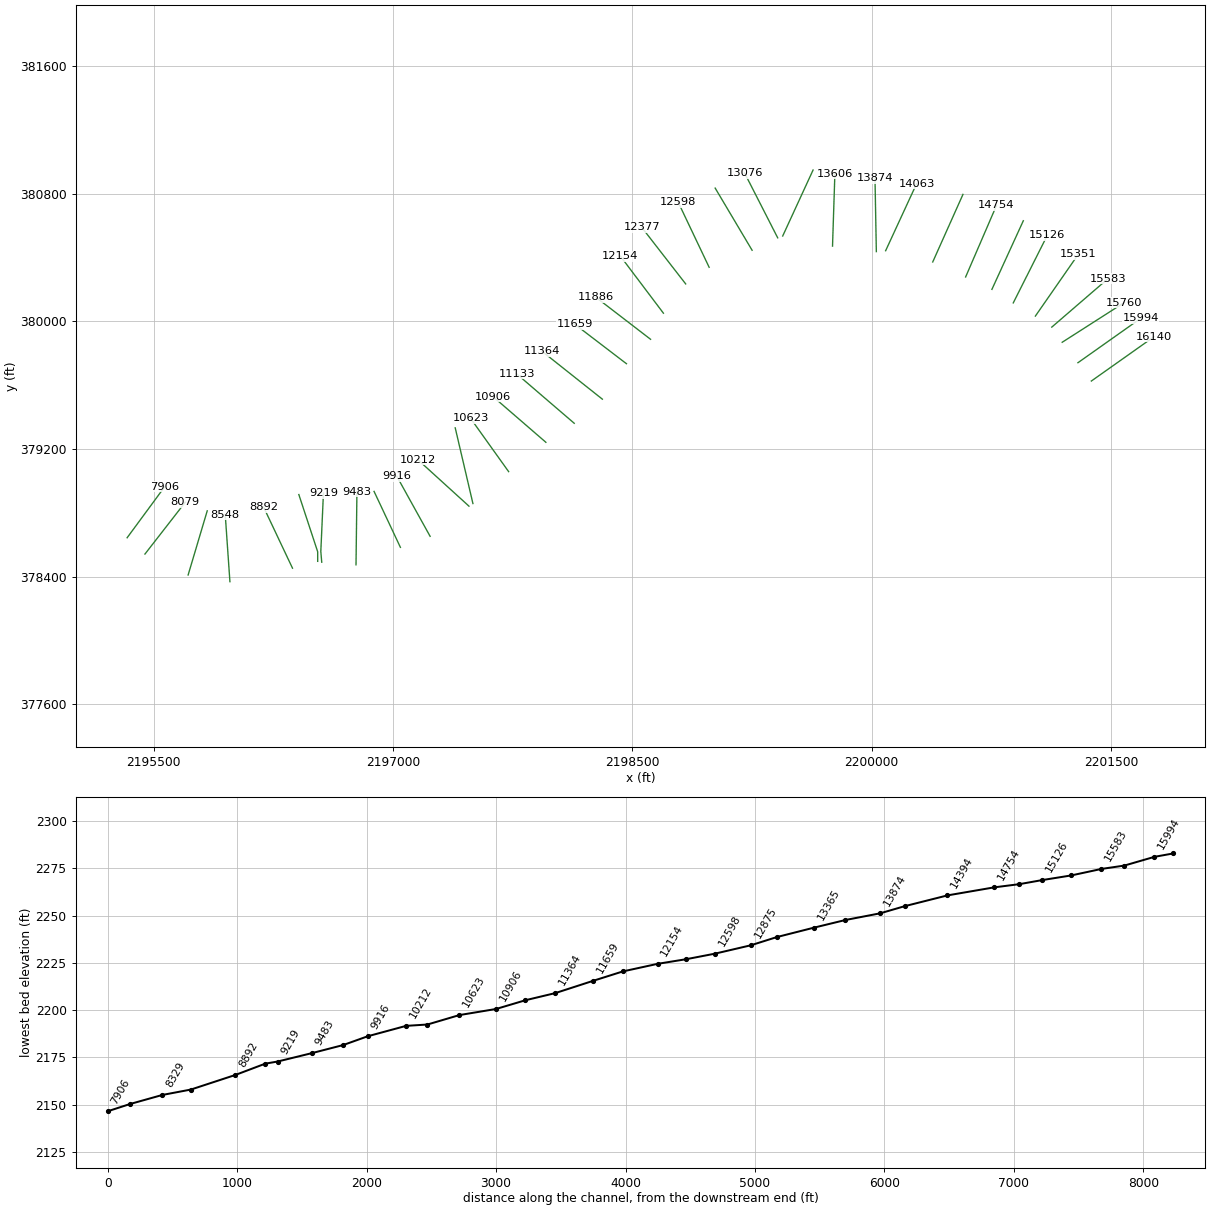
HEC-RAS study SPICERN.prj: SPICERN

--- SPICERN.g01 (geometry) --- (continued)

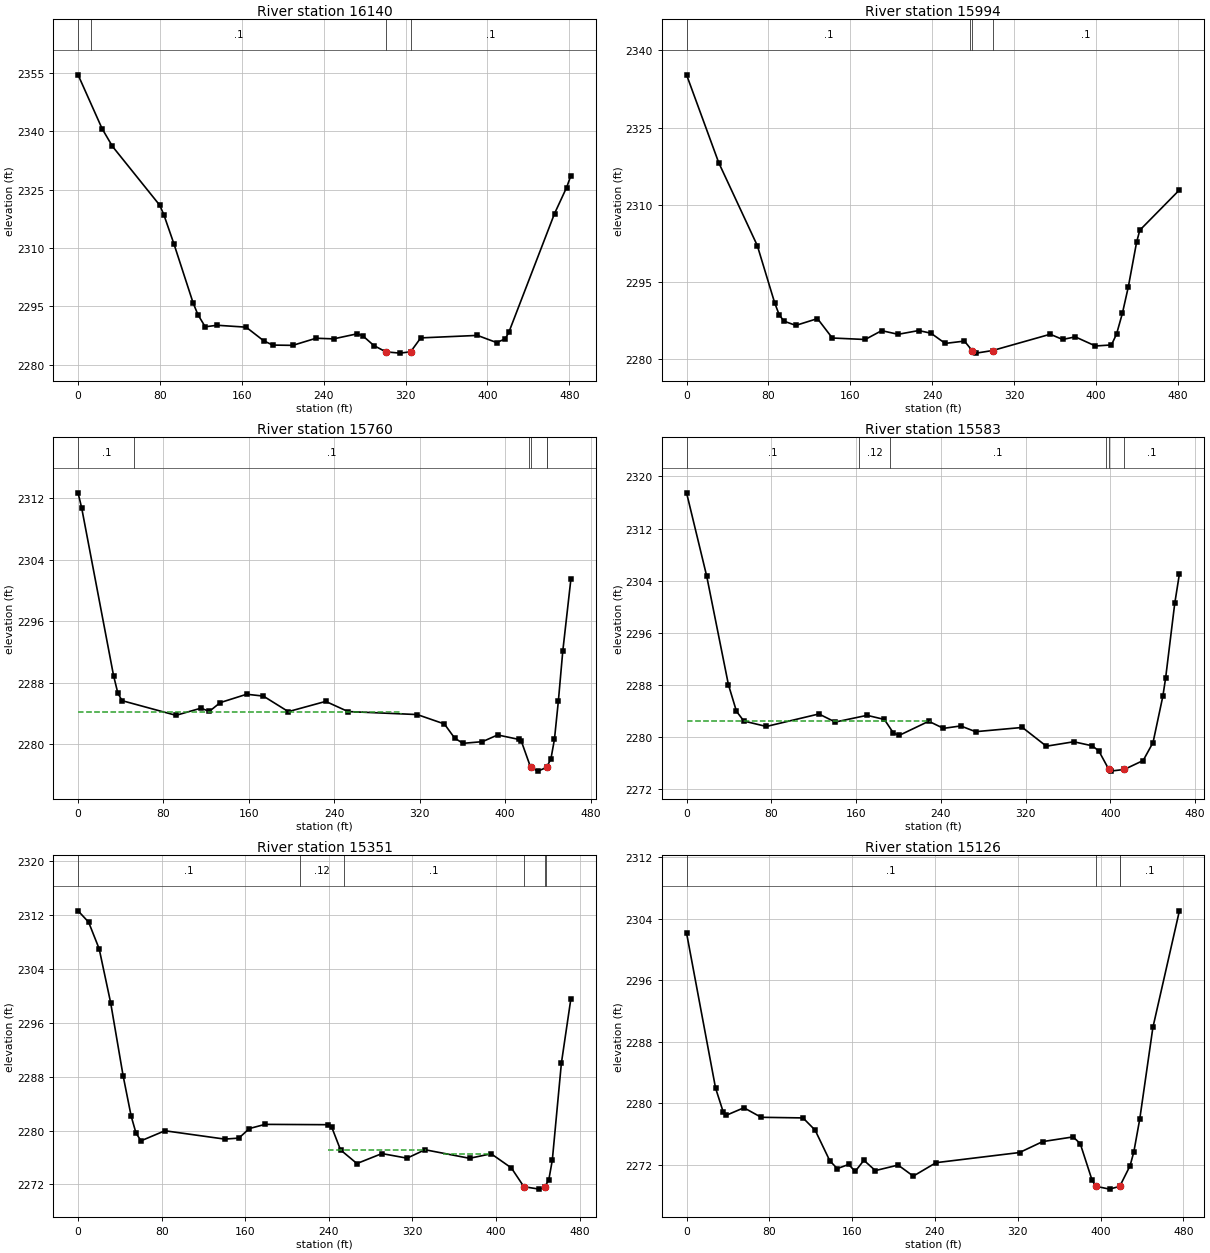
Type RM Length L Ch R = 1 ,16140   ,144.7,146.4,145.5
XS GIS Cut Line= 2
2201376.90904467379625.5544782962201770.09417435379903.522722583
#Sta/Elev= 30
       0 2354.57    23.5 2340.71    33.6 2336.16    79.8 2321.01    83.8 2318.58
    93.6 2311.12   112.4 2295.88   117.1 2292.85   124.2 2289.73     136 2290.12
   164.2 2289.63   181.4 2286.12   190.1 2285.02   209.8 2284.95   232.5 2286.78
   249.6 2286.62   272.5 2287.91     278 2287.45     289  2284.9   300.7 2283.28
   314.5 2282.95   324.9 2283.29   334.8 2286.87   390.2 2287.51     409 2285.66
   417.3 2286.63   420.8 2288.27   465.5 2318.86   477.3 2325.57   481.5 2328.65
#Mann= 4 ,-1 , 0
       0      .1       0   12.44      .1       0   300.7    .045       0
   324.9      .1       0
#XS Ineff= 2 , 0
                          388.13         2287.25
Permanent Ineff=
       F       F
Bank Sta=300.7,324.9
XS Rating Curve= 0 ,0
Exp/Cntr=0.3,0.1

Type RM Length L Ch R = 1 ,15994   ,232.3,233.3,225.6
XS GIS Cut Line= 2
2201292.98218365 379740.383644962201686.16731333380018.351889247
#Sta/Elev= 30
       0 2335.25    31.4 2318.18    69.1 2302.06    86.1 2290.91    90.4 2288.65
      95 2287.37   106.7 2286.53   127.9 2287.85   142.4 2284.08   174.5 2283.79
   190.6 2285.51   206.7  2284.8   226.8 2285.53   238.8 2285.01   252.7 2283.03
   271.5 2283.48     279 2281.63     283 2281.14   299.1 2281.65   355.3 2284.81
   367.4  2283.8   379.8  2284.3   399.5 2282.53   415.1 2282.73   420.1 2284.85
   425.8 2288.88   431.6 2294.03   439.7 2302.72   442.8 2305.04   481.5 2312.86
#Mann= 4 ,-1 , 0
       0      .1       0  277.37      .1       0     279    .045       0
   299.1      .1       0
Bank Sta=279,299.1
XS Rating Curve= 0 ,0
Exp/Cntr=0.3,0.1

Type RM Length L Ch R = 1 ,15760   ,175.8,176.9,177.9
XS GIS Cut Line= 2
2201194.15367791379868.5081283272201582.92695915380117.136653963
#Sta/Elev= 30
       0 2312.67     3.4  2310.7    33.3 2288.88    37.2 2286.68    41.1 2285.67
    91.7 2283.76   115.1 2284.69   122.9 2284.27   133.1 2285.41   157.9  2286.5
   173.5 2286.26   196.9 2284.24   231.9 2285.57   252.8 2284.25   317.6 2283.86
     343 2282.64   352.7 2280.79   360.5 2280.12   378.7 2280.34   392.9 2281.21
   413.2 2280.62     415 2280.43   423.8    2277   430.6 2276.51   438.72276.991
   442.8 2278.11   446.1 2280.65   449.8 2285.67   453.9 2292.11   461.5 2301.46
#Mann= 6 ,-1 , 0
       0      .1       0    52.8      .1       0  422.73      .1       0
   423.8    .045       0   438.7      .1       0  438.73      .1       0
#XS Ineff= 2 , 0
          302.23 2284.13
Permanent Ineff=
       F       F
Bank Sta=423.8,438.7
XS Rating Curve= 0 ,0
Exp/Cntr=0.3,0.1

Type RM Length L Ch R = 1 ,15583   ,229.7,232.7,234.4
XS GIS Cut Line= 2
2201129.09055267379963.6351263322201481.41531063380267.376071777
#Sta/Elev= 30
       0 2317.48      19 2304.69    39.5 2288.02    47.1 2283.92    54.1 2282.42
    75.3 2281.59   124.9 2283.51   140.3 2282.27   170.4  2283.3   186.7 2282.67
   195.3 2280.57   200.7 2280.22   228.6 2282.39   242.5  2281.3   258.8 2281.67
   272.8 2280.79     317 2281.44   339.6 2278.56   365.5 2279.24   382.9 2278.62
   389.1 2277.84   398.4 2275.05   400.2 2274.73   413.2 2274.99     431 2276.36
   440.3 2279.12   449.6 2286.25   452.2 2289.04   460.8 2300.49   465.2 2305.01
#Mann= 6 ,-1 , 0
       0      .1       0  163.21     .12       0  191.67      .1       0
  396.27      .1       0   398.4    .045       0   413.2      .1       0
#XS Ineff= 2 , 0
          229.86 2282.39
Permanent Ineff=
       F       F
Bank Sta=398.4,413.2
XS Rating Curve= 0 ,0
Exp/Cntr=0.3,0.1

Type RM Length L Ch R = 1 ,15351   ,222.1,224.3,225
XS GIS Cut Line= 2
2201026.16011236380032.7536789262201295.29342238 380420.14680004
#Sta/Elev= 30
       0 2312.64    10.1 2310.96    20.2    2307    31.2 2298.98    43.1 2288.16
    50.8 2282.16    55.5  2279.6    60.3 2278.48    83.1 2279.97   140.4 2278.73
   153.9 2278.88     164  2280.3     179 2280.92   238.9 2280.87   242.9 2280.46
   251.2 2277.13   266.9  2275.1   290.8 2276.58   314.9  2275.9   332.1 2277.15
   374.7 2275.88   395.4 2276.55   414.7 2274.45   426.7 2271.66   441.4  2271.3
   446.8 2271.61   450.6 2272.73   453.9 2275.59   462.6 2290.02   471.7  2299.6
#Mann= 6 ,-1 , 0
       0      .1       0  212.44     .12       0  254.09      .1       0
   426.7    .045       0   446.8      .1       0  448.12      .1       0
#XS Ineff= 2 ,-1
  238.86  332.69 2277.14  349.53  392.84 2276.51
Permanent Ineff=
       F       F
Bank Sta=426.7,446.8
XS Rating Curve= 0 ,0
Exp/Cntr=0.3,0.1

Type RM Length L Ch R = 1 ,15126   ,174.6,176,176
XS GIS Cut Line= 2
 2200887.4873723380115.3165239612201101.66818717380540.503074462
#Sta/Elev= 30
       0 2302.14      28 2281.99    35.4 2278.88    38.3 2278.44    55.4 2279.42
    72.1 2278.18   112.5  2278.1   124.2 2276.51   138.4 2272.52   145.6 2271.51
   156.6 2272.05   162.9 2271.14   171.3 2272.59   182.4 2271.25   204.4 2271.97
     219 2270.53     241 2272.28   321.7  2273.6     344 2275.02   373.4 2275.63
   380.3 2274.76   391.7 2270.02   395.4 2269.21   408.6 2268.84   418.52269.203
   428.5  2271.9   432.1  2273.7   437.8 2277.95   450.5 2289.87   476.1 2305.03
#Mann= 4 ,-1 , 0
       0      .1       0   395.4    .045       0   418.5      .1       0
  418.52      .1       0
Bank Sta=395.4,418.5
XS Rating Curve= 0 ,0
Exp/Cntr=0.3,0.1

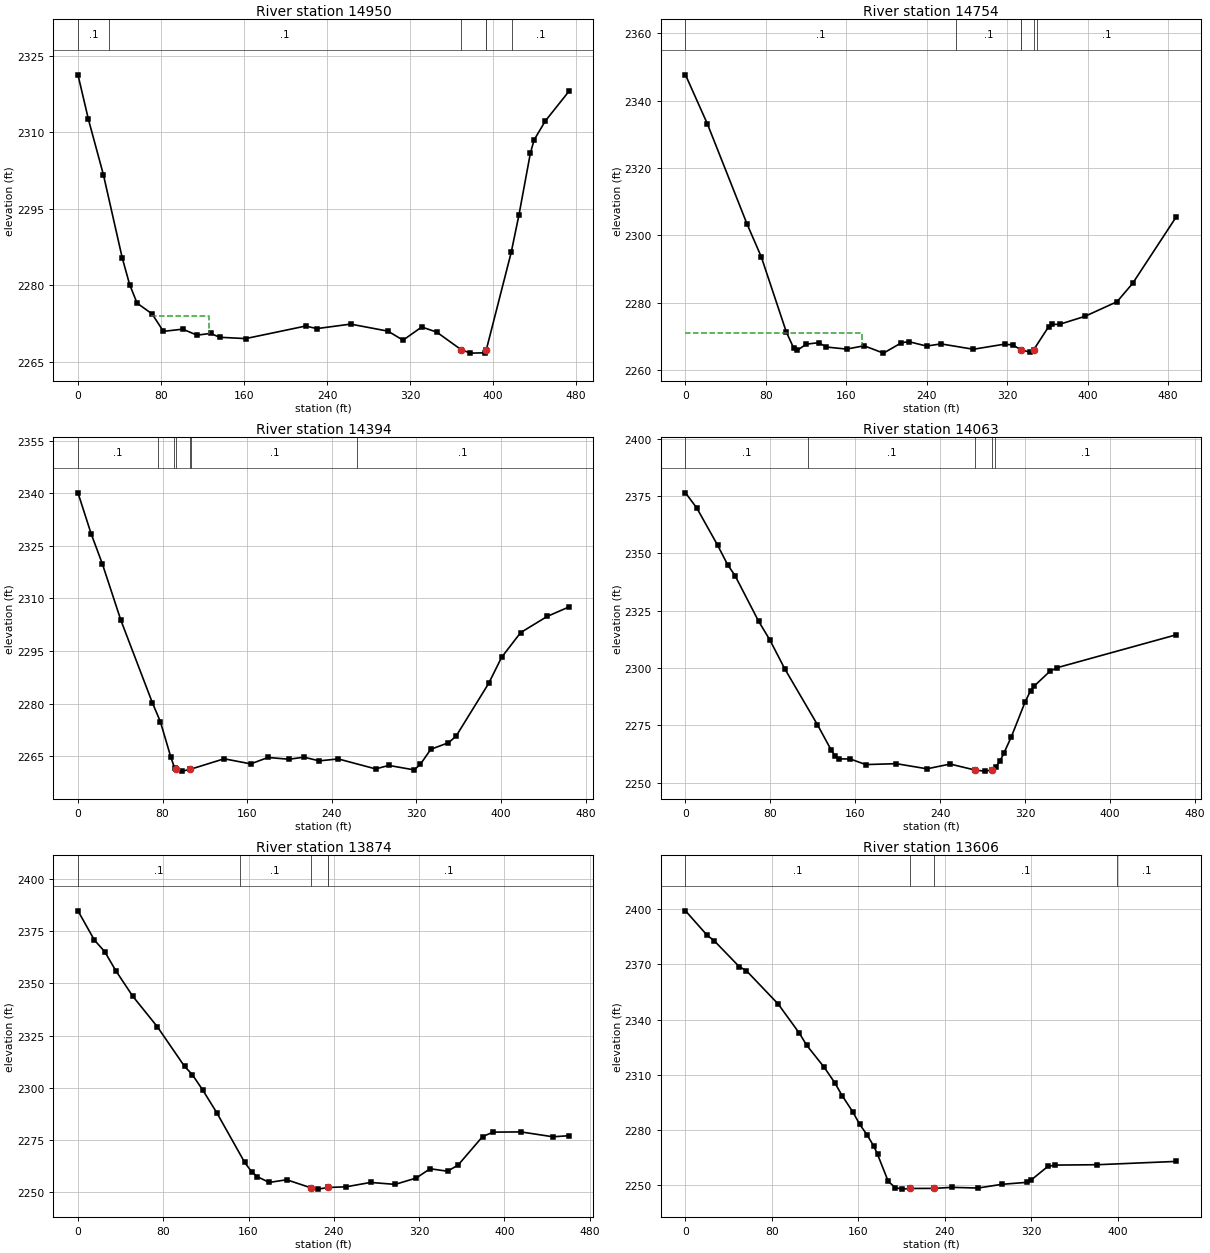
Type RM Length L Ch R = 1 ,14950   ,193.9,195.8,196.4
XS GIS Cut Line= 2
2200753.67599123380200.0846444282200950.53181369  380630.1828562
#Sta/Elev= 30
       0 2321.27    10.1 2312.51    24.5 2301.69    42.6 2285.42    49.8 2280.13
      57 2276.48    71.4 2274.39    82.3 2270.96     101 2271.39   114.7 2270.21
   127.8 2270.56   136.4  2269.8   161.6 2269.54   219.3    2272   230.2  2271.5
   262.7 2272.38   298.7    2271   313.2 2269.23   331.2 2271.81   345.6 2270.82
   369.1 2267.38   378.1 2266.69   392.6 2266.75   393.42267.317   417.4 2286.43
   424.8  2293.7   435.9 2305.92   439.5 2308.51   450.3 2312.22     473 2318.02
#Mann= 6 ,-1 , 0
       0      .1       0   30.06      .1       0   369.1    .045       0
   393.4      .1       0  393.43      .1       0  418.25      .1       0
#XS Ineff= 1 ,-1
   70.78  126.33  2273.9
Permanent Ineff=
       F
Bank Sta=369.1,393.4
XS Rating Curve= 0 ,0
Exp/Cntr=0.3,0.1

Type RM Length L Ch R = 1 ,14754   ,358.3,360.8,357.9
XS GIS Cut Line= 2
2200588.82125817380277.7029550682200782.39042483 380726.06980517
#Sta/Elev= 30
       0 2347.66    21.9 2333.01    61.2 2303.37    75.4 2293.59   100.3 2271.28
   107.8 2266.37   111.3 2265.86   120.3 2267.64   132.7 2268.09   139.9  2266.8
   160.2 2266.18   177.7 2267.16     197 2264.98   214.9 2268.06   222.1 2268.39
   239.9 2267.08   254.2 2267.72   286.4 2266.13   317.5 2267.65   325.7  2267.4
   333.62265.986   342.5 2265.29   346.3 2265.92   361.4 2272.88   364.7 2273.52
   372.1 2273.53   397.4 2275.91   429.3 2280.25   444.8 2285.67   488.4 2305.53
#Mann= 6 ,-1 , 0
       0      .1       0  268.92      .1       0  333.58      .1       0
   333.6    .045       0   346.3      .1       0  350.02      .1       0
#XS Ineff= 2 , 0
          175.38 2270.82
Permanent Ineff=
       F       F
Bank Sta=333.6,346.3
XS Rating Curve= 0 ,0
Exp/Cntr=0.3,0.1

Type RM Length L Ch R = 1 ,14394   ,327.9,330.1,329.2
XS GIS Cut Line= 2
2200382.70320681380371.7830293872200572.24158429 380795.53054378
#Sta/Elev= 30
       0 2340.13    12.4  2328.5    23.2 2319.75    40.6 2303.75    70.4  2280.2
    77.9 2274.86    87.8 2264.74    91.5 2261.53    92.8 2261.24    98.7 2260.73
   105.9 2261.22   138.2 2264.25   163.4  2262.8   179.7 2264.63   199.5 2264.12
   213.7 2264.71   228.1 2263.66   246.1 2264.21   281.5 2261.36   293.9 2262.36
   317.9 2261.08   323.7 2262.66   333.6 2266.95   350.3 2268.83   357.5 2270.69
   388.3 2285.74   400.6 2293.21   418.6 2300.26   443.7 2304.87   464.2 2307.56
#Mann= 7 ,-1 , 0
       0      .1       0   75.73      .1       0   90.95      .1       0
    92.8    .045       0   105.9      .1       0  107.06      .1       0
  264.31      .1       0
Bank Sta=92.8,105.9
XS Rating Curve= 0 ,0
Exp/Cntr=0.3,0.1

Type RM Length L Ch R = 1 ,14063   ,184.3,189.7,191.7
XS GIS Cut Line= 2
2200087.43546844380442.3418040832200281.36611385380862.115220113
#Sta/Elev= 30
       0 2376.47    10.7 2369.81    30.4  2353.5    39.6 2345.18    46.8 2340.24
    68.8  2320.5    79.4 2312.34    93.5 2299.68   124.3 2275.29   137.2 2264.28
   140.8  2261.8   144.4 2260.37   155.2 2260.34   169.7 2257.89   198.6 2258.28
   227.5 2256.04   249.3 2258.12   272.9 2255.48   281.7 2255.03     289 2255.52
   292.6 2257.01   296.3  2259.5   299.8 2262.77     307 2270.08   319.8 2285.12
   325.1 2290.18   328.7 2292.26   343.2 2298.57   350.4 2300.21   462.4 2314.54
#Mann= 5 ,-1 , 0
       0      .1       0  115.09      .1       0   272.9    .045       0
     289      .1       0  291.09      .1       0
Bank Sta=272.9,289
XS Rating Curve= 0 ,0
Exp/Cntr=0.3,0.1

Type RM Length L Ch R = 1 ,13874   ,267.9,267.9,267.2
XS GIS Cut Line= 2
2200029.22875782380436.7286718462200020.81386335380897.157232773
#Sta/Elev= 30
       0 2384.85    15.3 2370.89    25.2 2365.17    35.6 2356.02    51.4 2343.86
    74.4 2329.24     100 2310.17   107.2 2306.27     117 2298.85   130.2 2287.94
   156.4 2264.06     163 2259.54   168.1 2257.27   179.4 2254.46   195.8 2255.75
   218.32251.915   225.3 2251.25   234.32252.032   251.6 2252.37   274.5 2254.46
   297.5 2253.53   317.2 2256.55   330.3 2261.03   346.7 2259.85   356.6 2262.81
   379.5 2276.45   389.4 2278.62   415.6 2278.71   445.5 2276.38   460.5 2276.89
#Mann= 5 ,-1 , 0
       0      .1       0  151.74      .1       0   218.3    .045       0
   234.3      .1       0  234.32      .1       0
Bank Sta=218.3,234.3
XS Rating Curve= 0 ,0
Exp/Cntr=0.3,0.1

Type RM Length L Ch R = 1 ,13606   ,244.5,240.8,236.5
XS GIS Cut Line= 2
2199754.51384382 380471.273399832199769.36036736380925.323535446
#Sta/Elev= 30
       0  2399.2    20.1 2385.86    26.7 2382.84    49.7 2368.85    56.3 2366.64
    85.8 2348.46   105.5  2332.5   112.1 2326.07   128.5 2313.94   138.3 2305.48
   144.9 2298.67   154.7 2289.89   161.3  2282.9   167.9 2277.38   174.4 2270.96
   177.7 2266.69   187.6 2251.97   194.1 2248.55   200.7 2247.72   207.82248.079
   230.2 2248.13   246.6 2248.69   270.7 2248.31   292.6 2250.33   315.6 2251.39
   319.5 2252.51   335.3 2260.06   341.8  2260.8   381.2 2261.01   454.3 2262.81
#Mann= 4 ,-1 , 0
       0      .1       0   207.8    .045       0   230.2      .1       0
  399.72      .1       0
Bank Sta=207.8,230.2
XS Rating Curve= 0 ,0
Exp/Cntr=0.3,0.1

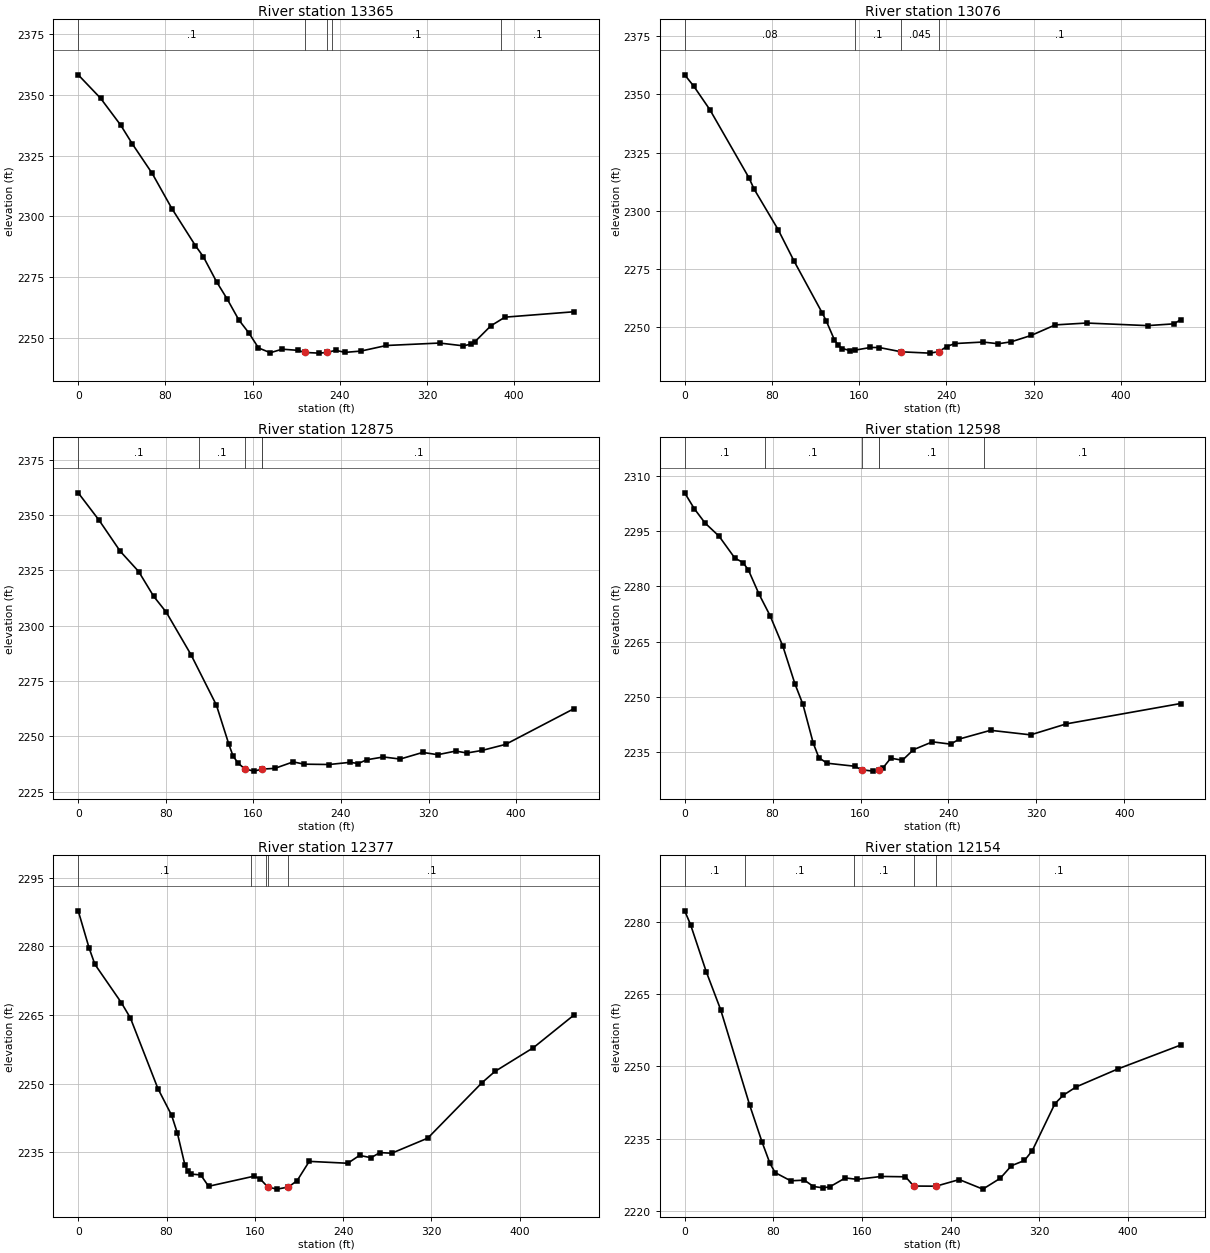
Type RM Length L Ch R = 1 ,13365   ,267.5,289.1,294.4
XS GIS Cut Line= 2
2199442.35405641380534.7246316442199632.59195219380948.098516486
#Sta/Elev= 30
       0 2358.24    20.5 2348.61      39 2337.52    49.8 2329.71    67.9 2317.65
    85.9 2303.22   107.6 2287.89   114.8 2283.39   126.9 2273.11   136.8 2265.88
   147.3 2257.41   156.6    2252   165.4 2245.85   176.2 2243.87   187.1 2245.33
   201.5 2244.86     208 2243.99   220.9 2243.71   228.3 2243.98   236.1 2244.86
   244.9 2244.02   259.3 2244.55   282.7 2246.85   331.5 2247.86   353.2 2246.72
   360.4 2247.39     364 2248.42   378.5 2254.92   391.5 2258.51     455 2260.74
#Mann= 5 ,-1 , 0
       0      .1       0     208    .045       0   228.3      .1       0
   232.4      .1       0  388.05      .1       0
#XS Ineff= 2 , 0
                          330.76         2247.83
Permanent Ineff=
       F       F
Bank Sta=208,228.3
XS Rating Curve= 0 ,0
Exp/Cntr=0.3,0.1

Type RM Length L Ch R = 1 ,13076   ,195.3,201,201.9
XS GIS Cut Line= 2
2199410.78491551380523.3384535982199203.92560504380928.490436104
#Sta/Elev= 30
       0 2358.45     8.4 2353.52    23.1 2343.45    58.9 2314.19    63.7 2309.26
    85.7 2291.86   100.3 2278.32   126.2 2255.96   129.9  2252.5   137.3 2244.46
     141 2241.99   144.7 2240.66   151.5 2239.81   156.4 2239.99   170.4 2241.12
   178.4 2241.11   198.7 2239.25   224.7 2238.69   233.1  2239.3   240.4 2241.54
   247.8 2242.81   273.6 2243.46   287.7 2242.73   299.4 2243.55   317.8  2246.3
   339.9 2250.84   368.6 2251.64   424.6 2250.53     449  2251.3   454.9  2253.1
#Mann= 4 ,-1 , 0
       0     .08       0   156.4      .1       0   198.7    .045       0
   233.1      .1       0
#XS Ineff= 2 , 0
                          272.48         2243.38
Permanent Ineff=
       F       F
Bank Sta=198.7,233.1
XS Rating Curve= 0 ,0
Exp/Cntr=0.3,0.1

Type RM Length L Ch R = 1 ,12875   ,277.6,277.2,276.1
XS GIS Cut Line= 2
2199250.37727999380445.2864384742199019.03903969380834.768757138
#Sta/Elev= 30
       0 2360.02    19.2 2347.55    38.4 2333.62    55.2 2324.49    68.9  2313.3
    80.4 2306.13     103 2286.94   126.2 2264.18   137.6 2246.46   141.4 2241.19
   146.1 2237.93   152.22235.338   160.5 2234.34   168.22235.256   179.6 2235.59
   196.4 2238.52   206.3 2237.48   229.2 2237.33   248.3 2238.31   255.9 2237.78
   263.5 2239.47   278.8 2240.73   294.1 2239.79   314.7 2242.79   328.4 2241.76
   344.8  2243.4   355.1 2242.53   368.8 2243.68   390.3  2246.4     453 2262.59
#Mann= 5 ,-1 , 0
       0      .1       0   110.7      .1       0   152.2    .045       0
   168.2      .1       0  168.22      .1       0
Bank Sta=152.2,168.2
XS Rating Curve= 0 ,0
Exp/Cntr=0.3,0.1

Type RM Length L Ch R = 1 ,12598   ,218.6,220.4,222.3
XS GIS Cut Line= 2
2198981.17943761380338.4844741642198787.41569235380745.966843699
#Sta/Elev= 30
       0 2305.32     8.7 2301.03    18.6 2297.12    31.3 2293.56    45.6 2287.65
    53.1 2286.41      58  2284.4    67.6 2277.89    77.7 2272.03    89.4  2263.7
   100.3 2253.57   107.6 2247.97     117 2237.45   122.1 2233.56   129.4 2232.06
   154.8 2231.23   160.9 2230.29   171.2 2229.91   176.92230.259   180.2 2230.72
   187.5 2233.42   198.1 2232.86   208.1 2235.71   225.4 2237.85     242 2237.22
     250 2238.62   278.3 2240.97   314.7 2239.74   347.3 2242.72   451.2 2248.23
#Mann= 6 ,-1 , 0
       0      .1       0   72.94      .1       0   160.9    .045       0
   176.9      .1       0  176.93      .1       0   272.4      .1       0
Bank Sta=160.9,176.9
XS Rating Curve= 0 ,0
Exp/Cntr=0.3,0.1

Type RM Length L Ch R = 1 ,12377   ,223.3,223.1,222.8
XS GIS Cut Line= 2
2198834.05042851 380234.269134692198558.49671084380589.157013675
#Sta/Elev= 30
       0 2287.77     9.9 2279.62    15.1 2276.09      39 2267.74    47.3 2264.36
    72.2 2248.96    84.6 2243.14    89.9 2239.17    96.7 2232.23    99.3 2230.96
   102.1 2230.29     111  2230.1   118.1 2227.62   159.4 2229.83   164.7 2229.26
   171.8 2227.45   180.2    2227   190.5 2227.46   198.4 2228.88   209.3 2233.06
   244.2 2232.65   254.9 2234.37   265.3 2233.86   273.3 2234.98     284 2234.84
   316.7 2238.14   365.8 2250.24   377.5 2252.69   412.4 2257.89   449.3 2265.05
#Mann= 5 ,-1 , 0
       0      .1       0  156.38      .1       0  170.26      .1       0
   171.8    .045       0   190.5      .1       0
Bank Sta=171.8,190.5
XS Rating Curve= 0 ,0
Exp/Cntr=0.3,0.1

Type RM Length L Ch R = 1 ,12154   ,268,268.4,270.5
XS GIS Cut Line= 2
2198694.52805022380050.856479041 2198425.1217613380408.056345553
#Sta/Elev= 30
       0 2282.25     5.3 2279.39    19.4 2269.66    32.4 2261.78    58.7  2241.9
    69.9 2234.22    76.9 2229.88    81.6 2227.95    95.6 2226.25     108 2226.38
   116.2 2225.06   124.4  2224.8   130.8 2224.98   144.9 2226.84   155.6 2226.55
   177.4 2227.15   199.2 2227.08   206.6 2225.16   226.8 2225.13   247.7  2226.5
     269 2224.52   284.7 2226.77   294.8 2229.38   306.5 2230.46   313.6 2232.51
     334 2242.25   341.6 2244.01   353.3 2245.74   390.8 2249.45   447.4  2254.4
#Mann= 5 ,-1 , 0
       0      .1       0   54.76      .1       0  152.84      .1       0
   206.6    .045       0   226.8      .1       0
Bank Sta=206.6,226.8
XS Rating Curve= 0 ,0
Exp/Cntr=0.3,0.1

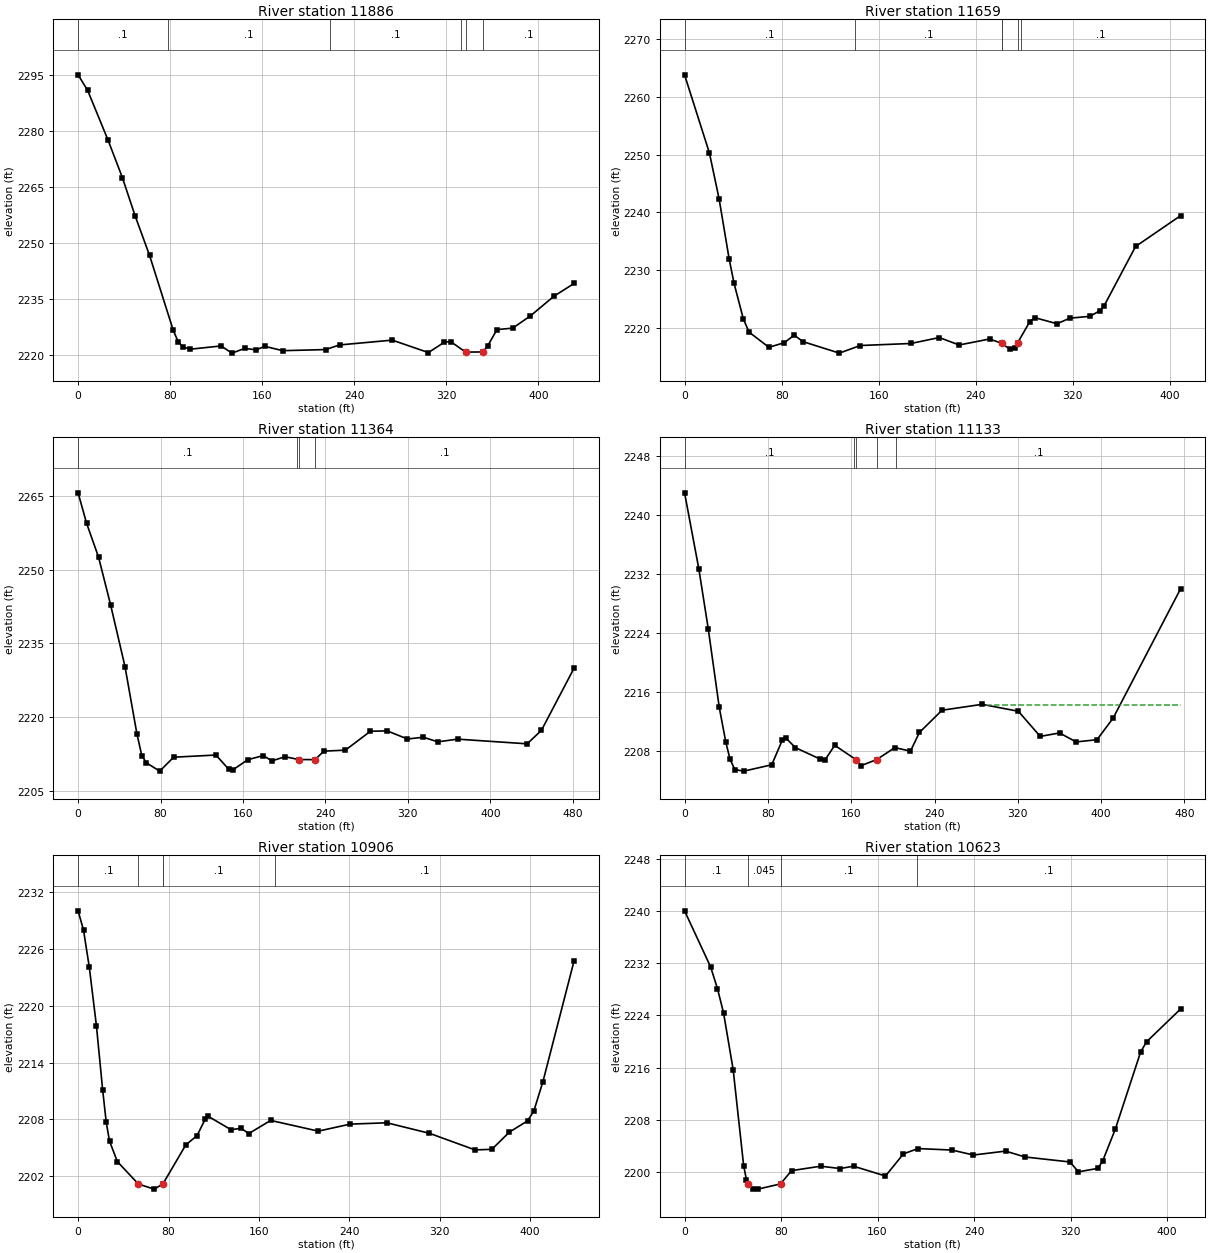
Type RM Length L Ch R = 1 ,11886   ,227.7,227,228.2
XS GIS Cut Line= 2
 2198613.9669773379887.2744806912198272.07664704380149.965868895
#Sta/Elev= 30
       0    2295     8.3 2290.83    26.1 2277.47    38.5 2267.49    49.6 2257.22
    62.1 2246.69    82.7 2226.63    86.9 2223.62      91 2222.18    97.7 2221.57
   124.3 2222.43   133.7 2220.51   144.8 2221.77   154.8  2221.4   162.3 2222.32
   177.9 2221.17   215.1 2221.46   227.3  2222.7   273.1 2223.99   304.5 2220.66
   318.5 2223.46   323.9  2223.6   336.8 2220.79   351.7 2220.82     356  2222.4
   364.1 2226.82   377.7 2227.19   393.1 2230.45   413.7 2235.76   431.2 2239.17
#Mann= 6 ,-1 , 0
       0      .1       0   77.95      .1       0  219.23      .1       0
  333.17      .1       0   336.8    .045       0   351.7      .1       0
Bank Sta=336.8,351.7
XS Rating Curve= 0 ,0
Exp/Cntr=0.3,0.1

Type RM Length L Ch R = 1 ,11659   ,294.1,294.9,293
XS GIS Cut Line= 2
2198462.69505369379734.2179238422198137.89255369379982.411875804
#Sta/Elev= 30
       0 2263.83    20.5 2250.27    28.5 2242.29    36.7 2231.97    40.8 2227.68
    48.4 2221.55    53.1 2219.24    69.5  2216.6    82.1 2217.39    90.4  2218.7
    97.6 2217.58   127.6 2215.59   144.8 2216.91   186.5 2217.26   209.9 2218.29
   226.3    2217   251.4 2218.04   261.4 2217.29   268.4 2216.22   272.1  2216.5
   274.5 2217.38   284.5 2221.04   288.6 2221.74   306.9 2220.69   317.6 2221.65
     334 2221.97   342.3 2222.94   345.7 2223.77   371.7 2234.08   408.8 2239.42
#Mann= 6 ,-1 , 0
       0      .1       0   140.4      .1       0  261.39      .1       0
   261.4    .045       0   274.5      .1       0  277.58      .1       0
Bank Sta=261.4,274.5
XS Rating Curve= 0 ,0
Exp/Cntr=0.3,0.1

Type RM Length L Ch R = 1 ,11364   ,230.8,230.9,229.3
XS GIS Cut Line= 2
2198311.83781431379511.883414822 2197934.8344773379811.095980366
#Sta/Elev= 30
       0  2265.6     8.2 2259.44    19.8 2252.56    31.5 2242.87    45.5 2230.29
    57.1 2216.59    61.8 2212.21    66.3 2210.72    79.2 2209.04    92.7 2211.87
   133.7 2212.31   146.2 2209.42   150.4 2209.33   164.6 2211.36   179.7  2212.2
   188.1 2211.12   200.7 2211.97   214.1  2211.4   229.9 2211.37   238.4  2213.1
   259.3  2213.3   283.7 2217.15     300 2217.21   319.6 2215.57     335 2215.93
     349 2214.99   368.2 2215.54   435.7 2214.59   449.5 2217.31   481.3    2230
#Mann= 4 ,-1 , 0
       0      .1       0  212.36      .1       0   214.1    .045       0
   229.9      .1       0
Bank Sta=214.1,229.9
XS Rating Curve= 0 ,0
Exp/Cntr=0.3,0.1

Type RM Length L Ch R = 1 ,11133   ,228.1,226.5,227.3
XS GIS Cut Line= 2
2198135.51185879379360.7713621812197774.07364397379670.991547358
#Sta/Elev= 30
       0 2243.01    13.7  2232.7    22.8 2224.52    33.3 2213.92    39.6  2209.2
    43.7 2206.85    48.3 2205.46    56.9 2205.26    83.7 2206.12    93.8 2209.44
    97.2 2209.76   106.5 2208.44   129.8 2206.92   134.8 2206.77   144.2 2208.76
     165 2206.78   169.4    2206   184.5 2206.83   201.9 2208.45   216.9 2207.97
   225.5  2210.5   247.2 2213.52   285.7 2214.32   320.5 2213.38   341.5 2209.97
   360.1 2210.44   375.9 2209.22     396 2209.52   411.5 2212.45   476.3    2230
#Mann= 5 ,-1 , 0
       0      .1       0  162.64      .1       0     165    .045       0
   184.5      .1       0  203.14      .1       0
#XS Ineff= 2 , 0
                          289.34         2214.23
Permanent Ineff=
       F       F
Bank Sta=165,184.5
XS Rating Curve= 0 ,0
Exp/Cntr=0.3,0.1

Type RM Length L Ch R = 1 ,10906   ,286.4,283.6,281
XS GIS Cut Line= 2
2197957.80031063379241.5268166922197625.69677798 379528.54498827
#Sta/Elev= 30
       0 2230.01     4.8 2227.98     9.9 2224.07    16.2  2217.9    21.7 2211.15
    24.9 2207.69    27.8 2205.71    34.7 2203.55    53.4 2201.17    67.4 2200.64
    75.1  2201.2    95.3 2205.31   105.2 2206.28   112.7 2208.08   115.2 2208.32
   135.3 2206.91   144.1 2207.06   151.1 2206.51   170.4 2207.89   212.5 2206.76
   240.7  2207.5   273.2 2207.64   310.9 2206.53   351.2 2204.78   366.1 2204.84
   381.6 2206.66   397.7 2207.84   403.3 2208.91   411.3 2211.99   438.9 2224.76
#Mann= 5 ,-1 , 0
       0      .1       0    53.4    .045       0    75.1      .1       0
   75.53      .1       0  174.15      .1       0
#XS Ineff= 2 , 0
                          115.68         2208.17
Permanent Ineff=
       F       F
Bank Sta=53.4,75.1
XS Rating Curve= 0 ,0
Exp/Cntr=0.3,0.1

Type RM Length L Ch R = 1 ,10623   ,249.8,246.7,237.5
XS GIS Cut Line= 2
2197724.31807087379057.6879418422197485.13522437379392.332941844
#Sta/Elev= 30
       0 2240.01    21.6 2231.43    27.3 2228.09    32.3 2224.41    40.3  2215.7
      49    2201    51.3 2198.86    52.62198.214    56.5 2197.42    60.8 2197.41
    79.6 2198.21    88.7 2200.24   112.9 2200.92     129 2200.56   140.1 2200.92
   166.6 2199.42   181.5 2202.81   193.6 2203.62   221.8 2203.39   239.5 2202.63
   266.2 2203.23   282.3 2202.33   319.5 2201.57   326.6 2200.06   342.8 2200.59
   346.8 2201.78   357.1 2206.57   378.2 2218.43   383.1 2219.97   411.3 2224.99
#Mann= 4 ,-1 , 0
       0      .1       0    52.6    .045       0    79.6      .1       0
  193.09      .1       0
#XS Ineff= 2 , 0
                          200.54         2203.39
Permanent Ineff=
       F       F
Bank Sta=52.6,79.6
XS Rating Curve= 0 ,0
Exp/Cntr=0.3,0.1

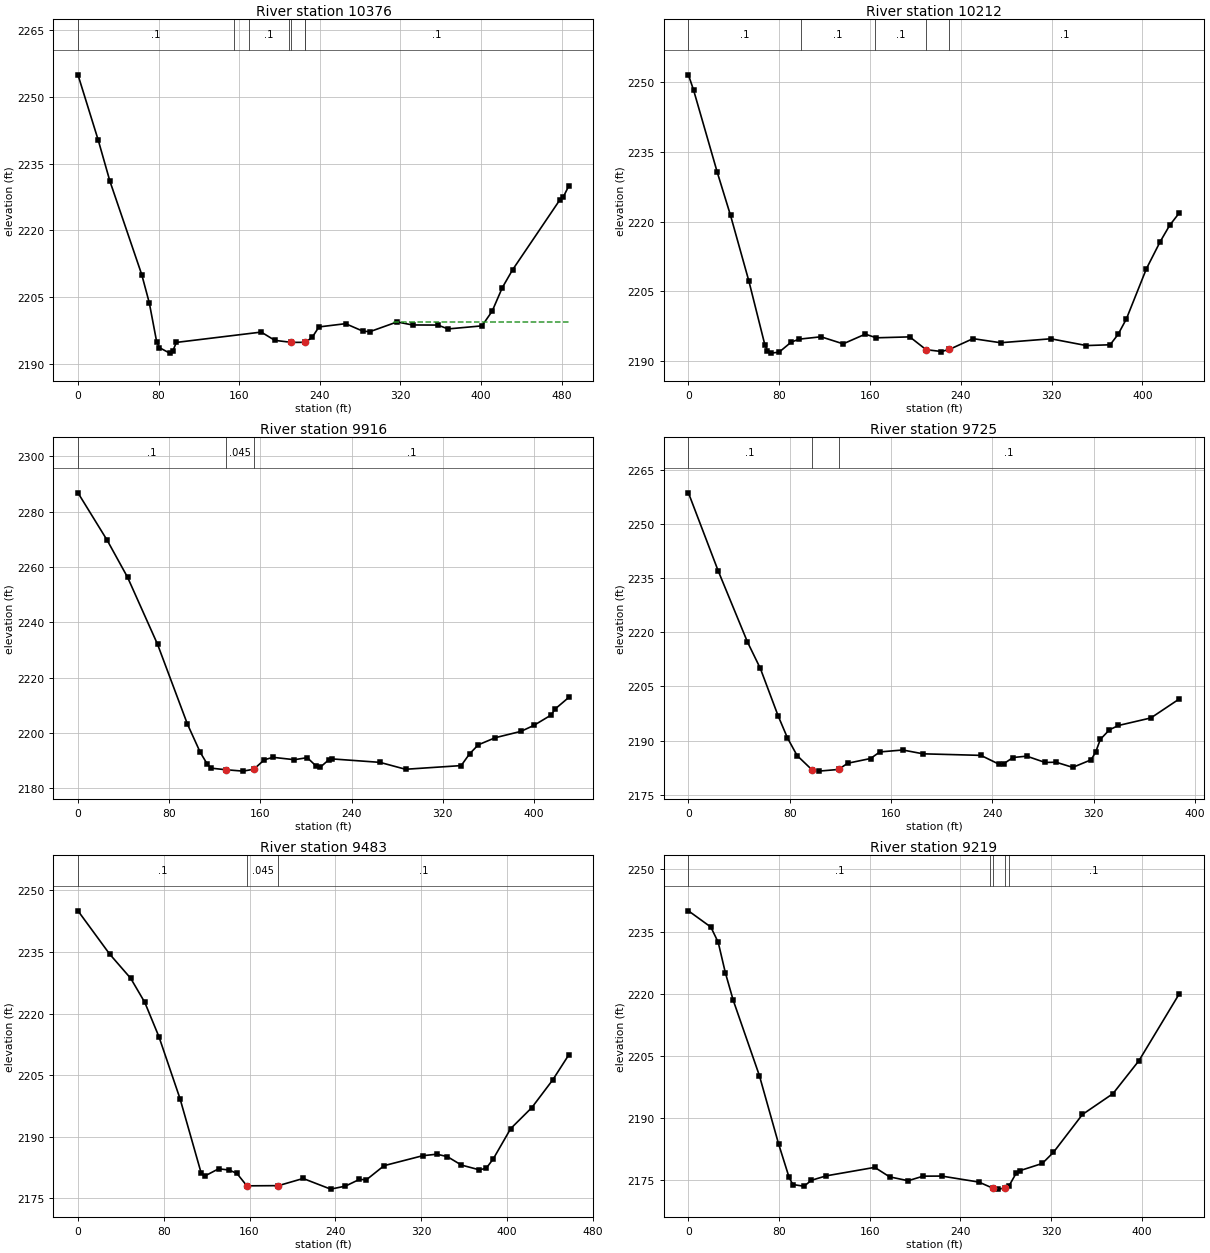
Type RM Length L Ch R = 1 ,10376   ,159.3,164.5,169.5
XS GIS Cut Line= 2
2197500.46926045378857.5571085132197389.49754558379332.087798053
#Sta/Elev= 30
       0 2254.99    20.2 2240.24    31.7 2231.08    63.3 2210.07    70.8 2203.72
    78.1 2194.99    80.8 2193.66      91 2192.42    94.3    2193    97.7 2194.83
   181.9 2197.15   195.4 2195.29   211.9 2194.84   225.72194.843   232.5 2195.98
   239.2 2198.31   265.6 2199.04   282.9 2197.35   289.8 2197.25   316.7 2199.43
   332.1 2198.75   357.2 2198.73   367.3 2197.86     401 2198.55   411.1 2201.85
   421.2 2207.15   431.3 2211.13   478.4 2226.91   481.8 2227.57   487.3 2230.08
#Mann= 7 ,-1 , 0
       0      .1       0  154.55      .1       0     170      .1       0
  209.71      .1       0   211.9    .045       0   225.7      .1       0
  225.73      .1       0
#XS Ineff= 2 , 0
                          313.54         2199.34
Permanent Ineff=
       F       F
Bank Sta=211.9,225.7
XS Rating Curve= 0 ,0
Exp/Cntr=0.3,0.1

Type RM Length L Ch R = 1 ,10212   ,299.3,296,291.4
XS GIS Cut Line= 2
2197475.57851852378841.3597295782197155.53578694379132.277807743
#Sta/Elev= 30
       0 2251.65     4.6 2248.32    25.4 2230.67    37.1 2221.37    53.3 2207.19
    67.3 2193.53    69.6 2192.26    72.9 2191.71    79.9 2191.92    90.5 2194.07
    97.6 2194.72   116.8 2195.23   136.3 2193.71   155.8  2195.8   165.5 2195.01
     195 2195.21   209.4 2192.45   222.9 2192.06   229.8  2192.5   250.7 2194.83
     275 2193.95   319.3  2194.8   350.6 2193.34   371.5 2193.51   378.5 2195.75
   385.8 2199.07   403.5 2209.91   415.6 2215.72     424 2219.26   432.5 2221.93
#Mann= 5 ,-1 , 0
       0      .1       0   98.77      .1       0  164.79      .1       0
   209.4    .045       0   229.8      .1       0
Bank Sta=209.4,229.8
XS Rating Curve= 0 ,0
Exp/Cntr=0.3,0.1

Type RM Length L Ch R = 1 ,9916    ,190.6,190.6,189.3
XS GIS Cut Line= 2
2197232.05784108378652.1867974832197023.28884179379028.798347502
#Sta/Elev= 30
       0  2286.8    25.7  2269.6    43.5 2256.28    69.8 2232.06      96 2203.22
   107.3 2192.96   113.6 2188.62   116.8 2187.29   129.8 2186.72   144.8 2186.22
   154.2 2186.91   163.5 2190.32     171 2191.21   189.8 2190.35   201.1 2191.09
   208.5  2188.2   212.3 2187.54   219.8 2190.27     223 2190.63   264.8 2189.39
   287.3 2186.89   336.1 2188.22   343.4 2192.43   351.1 2195.73   366.1 2198.31
   388.6  2200.6   399.9 2202.76   414.9 2206.47   418.6 2208.71   430.6 2212.91
#Mann= 3 ,-1 , 0
       0      .1       0   129.8    .045       0   154.2      .1       0
Bank Sta=129.8,154.2
XS Rating Curve= 0 ,0
Exp/Cntr=0.3,0.1

Type RM Length L Ch R = 1 ,9725    ,245.9,241.8,235.3
XS GIS Cut Line= 2
2197045.89931319 378583.059270442196880.77940746378933.728789655
#Sta/Elev= 30
       0 2258.56    23.5 2236.97    46.6  2217.3    56.8 2209.95    70.8 2196.87
    78.2 2190.73    85.8 2185.86    97.42181.965   102.9 2181.55   118.5 2182.01
   125.7 2183.73   143.8 2185.04   151.1 2186.86   169.2  2187.4   185.2 2186.34
   230.9 2185.91   245.4 2183.43     249 2183.62   256.3 2185.32   267.1 2185.69
   281.6 2183.95   290.2 2184.02   303.4 2182.59   317.9 2184.68   321.5 2186.81
   325.2 2190.34   332.4 2192.99   339.5 2194.18   365.1 2196.27   387.6 2201.54
#Mann= 3 ,-1 , 0
       0      .1       0    97.4    .045       0   118.5      .1       0
Bank Sta=97.4,118.5
XS Rating Curve= 0 ,0
Exp/Cntr=0.3,0.1

Type RM Length L Ch R = 1 ,9483    ,269.3,264.3,258.3
XS GIS Cut Line= 2
2196767.67485214378473.699608503 2196773.4194773 378931.53165227
#Sta/Elev= 30
       0    2245    29.5 2234.49    49.2 2228.57    62.3 2222.73    75.5 2214.38
    95.2 2199.28   114.8 2181.29   118.1 2180.44   131.2 2182.23   141.1 2181.92
   148.3 2181.09   157.5 2178.08     187 2178.13     210 2179.87   235.7 2177.28
   249.4 2178.01   262.5 2179.65     269 2179.55   285.5 2182.99   321.5 2185.41
   334.7 2185.78   344.5 2185.19   357.6 2183.14     374    2182   380.6 2182.31
   387.2 2184.58   403.6 2192.01   423.3 2197.12   442.8 2203.86   457.9    2210
#Mann= 3 ,-1 , 0
       0      .1       0   157.5    .045       0     187      .1       0
#XS Ineff= 2 , 0
                          335.56         2185.51
Permanent Ineff=
       F       F
Bank Sta=157.5,187
XS Rating Curve= 0 ,0
Exp/Cntr=0.3,0.1

Type RM Length L Ch R = 1 ,9219    ,92.6,95.2,97.8
XS GIS Cut Line= 3
 2196552.7187859378490.103775169 2196547.0419773378557.602447077
2196563.44614397378922.698967802
#Sta/Elev= 30
       0 2239.99    19.8 2236.07    26.3 2232.38    32.6 2225.04    39.5 2218.44
    62.6 2200.25    79.5 2183.81    88.8  2175.7    92.1 2173.95     102 2173.53
   108.5 2174.97   121.7 2176.05   164.4 2178.09   177.5  2175.8   193.9 2174.87
   207.1 2175.97   223.5 2175.99   256.3 2174.54   268.6 2173.07   273.4 2172.84
   279.7 2173.12   282.6 2173.49   289.2 2176.69   292.2 2177.27   312.2 2179.03
     322 2181.69   347.7 2190.86   374.6 2195.88   397.6 2203.86   433.2 2220.01
#Mann= 5 ,-1 , 0
       0      .1       0  266.46      .1       0   268.6    .045       0
   279.7      .1       0  282.58      .1       0
Bank Sta=268.6,279.7
XS Rating Curve= 0 ,0
Exp/Cntr=0.3,0.1

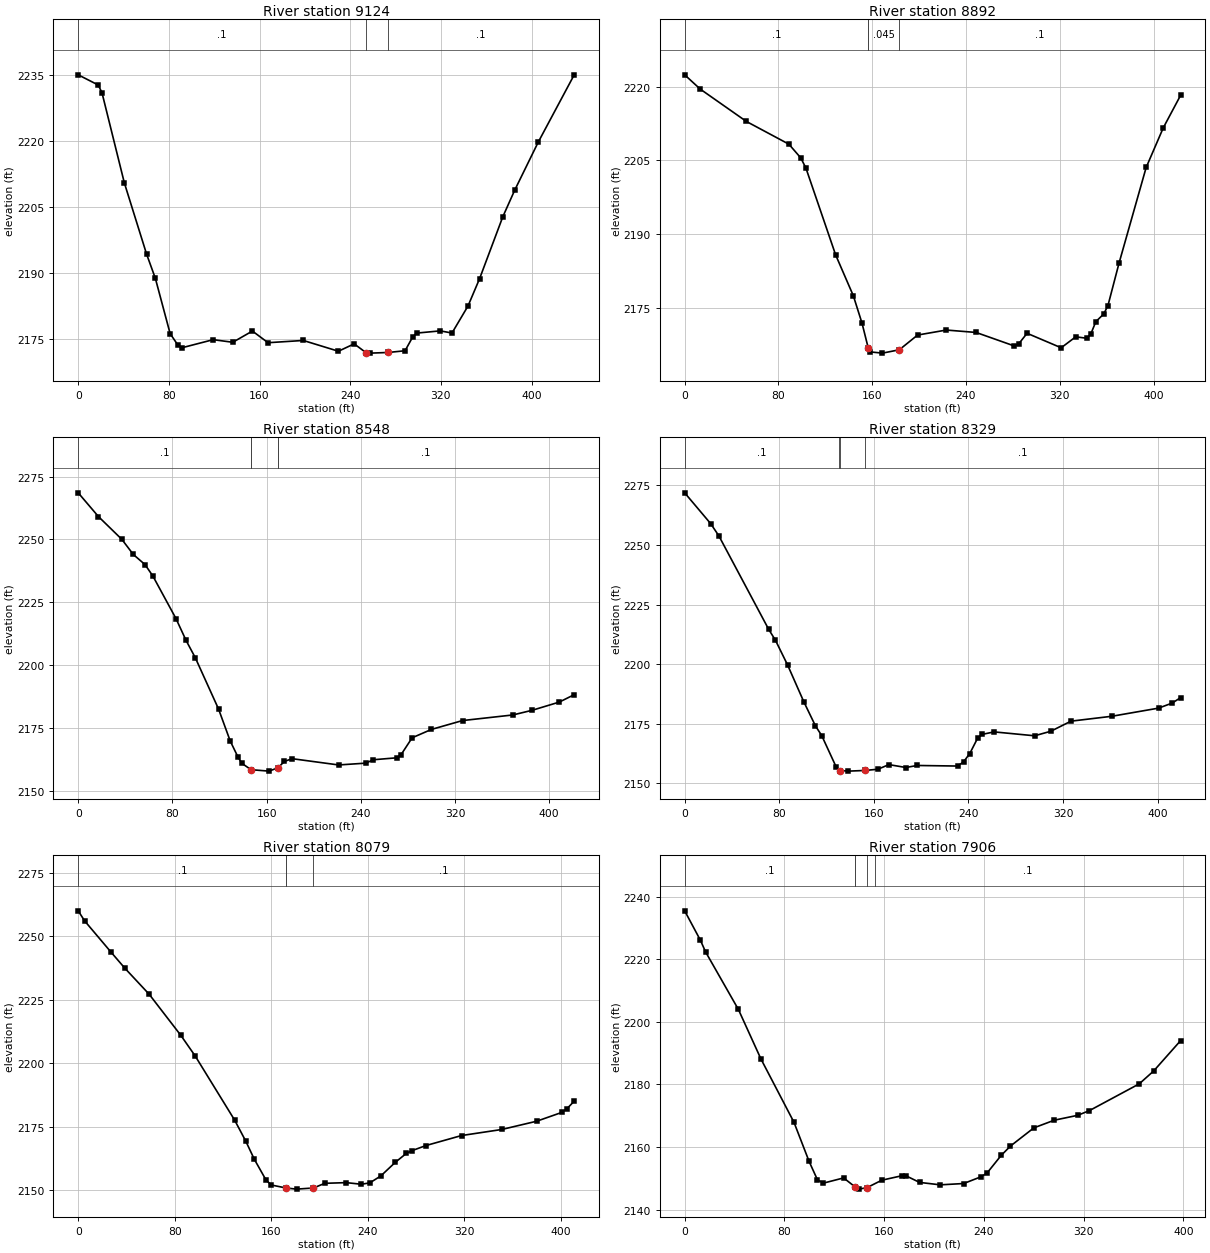
Type RM Length L Ch R = 1 ,9124    ,229.9,231.1,229.8
XS GIS Cut Line= 3
 2196527.3569773 378495.34565653 2196527.3569773378555.320855071
 2196409.2469773  378913.9807876
#Sta/Elev= 30
       0 2235.01    17.7 2232.69      21 2230.91    40.7 2210.44    60.3 2194.26
    68.1  2188.7    81.1 2176.16      88 2173.53    91.5 2172.94   119.1 2174.78
   136.4 2174.19   153.7 2176.74   167.5 2174.09   198.6  2174.6   229.6 2172.15
   243.5 2173.83   253.8 2171.85   257.8 2171.72   273.42171.867   288.4 2172.26
   295.3 2175.47   298.7 2176.28   319.5 2176.78   329.8 2176.29   343.9 2182.42
   354.2 2188.68   374.6  2202.7   385.1 2208.75   405.8 2219.65   437.6 2234.99
#Mann= 3 ,-1 , 0
       0      .1       0   253.8    .045       0   273.4      .1       0
Bank Sta=253.8,273.4
XS Rating Curve= 0 ,0
Exp/Cntr=0.3,0.1

Type RM Length L Ch R = 1 ,8892    ,347.5,344.1,338.1
XS GIS Cut Line= 2
2196369.53971818378452.4052059522196188.63649808378834.886418517
#Sta/Elev= 30
       0  2222.4    13.3 2219.49    52.7  2212.9    88.9 2208.28      99  2205.5
   103.4 2203.44   128.8 2185.73   143.9 2177.41   151.3 2171.83   156.72166.694
   157.8    2166   168.7 2165.74   183.1 2166.42   198.7 2169.42   223.2 2170.44
   248.6 2169.95   281.2  2167.2   284.9 2167.61   292.1 2169.78   321.2 2166.83
   333.6 2169.06   343.4 2168.76   346.6 2169.71   350.8 2172.16   357.5 2173.71
   361.1 2175.42   370.5 2184.01   393.7 2203.54   408.3 2211.61   423.1 2218.24
#Mann= 4 ,-1 , 0
       0      .1       0  156.67      .1       0   156.7    .045       0
   183.1      .1       0
Bank Sta=156.7,183.1
XS Rating Curve= 0 ,0
Exp/Cntr=0.3,0.1

Type RM Length L Ch R = 1 ,8548    ,222.3,219.8,213.9
XS GIS Cut Line= 2
2195977.25307943378367.916790332 2195947.8787117378788.096271829
#Sta/Elev= 30
       0 2268.52    17.2 2259.08      37 2250.07    46.8 2244.04    56.7 2240.04
    63.3 2235.57      83 2218.61    91.6 2209.91    99.5 2202.98   119.2 2182.65
   129.1 2169.97   135.6 2163.69   138.9 2161.14   146.82158.577     162 2158.01
   169.62159.313   175.1 2161.86   181.7 2162.95   221.2 2160.46   244.2 2161.18
   250.7 2162.53   270.5  2163.3   273.8 2164.26   283.6 2171.25   299.9 2174.56
   326.4 2178.09   369.1 2180.31   385.6 2182.18   408.6 2185.43   421.2 2188.36
#Mann= 5 ,-1 , 0
       0      .1       0  146.77      .1       0   146.8    .045       0
   169.6      .1       0  169.63      .1       0
Bank Sta=146.8,169.6
XS Rating Curve= 0 ,0
Exp/Cntr=0.3,0.1

Type RM Length L Ch R = 1 ,8329    ,252.1,249.7,243.9
XS GIS Cut Line= 2
2195715.32467736  378409.93489852195835.01624865 378811.89813897
#Sta/Elev= 30
       0 2271.85      22 2258.92    28.9 2253.81    71.1 2214.55    76.8    2210
    87.1 2199.59   100.8 2184.18   110.6 2174.12   115.9 2170.05   128.1 2156.92
   131.3 2155.42   138.4 2155.16   152.1 2155.43   163.4 2155.95   172.7 2157.89
   187.1 2156.68   196.6 2157.53   230.8 2157.29   235.8 2159.03   241.1 2162.54
   247.8 2169.05   251.4 2170.55   261.7 2171.61   295.9 2169.98   309.6 2171.88
   326.7 2176.11   361.2 2178.16   400.8 2181.58   412.3  2183.7   419.4 2185.98
#Mann= 4 ,-1 , 0
       0      .1       0  130.54      .1       0   131.3    .045       0
   152.1      .1       0
Bank Sta=131.3,152.1
XS Rating Curve= 0 ,0
Exp/Cntr=0.3,0.1

Type RM Length L Ch R = 1 ,8079    ,169.1,172.5,172.6
XS GIS Cut Line= 2
 2195444.6819773378541.0530352342195697.30614397378865.591648933
#Sta/Elev= 30
       0    2260     5.3 2256.05    26.9  2243.9    38.5 2237.49    58.8 2227.16
    85.1 2210.95      97 2202.83   129.7 2177.58   138.9 2169.33     146 2162.18
   155.8 2153.92   160.2 2151.99   172.72150.788   181.1 2150.37   195.1 2150.82
   204.5 2152.66   222.3 2152.93   234.9 2152.29   241.9 2152.85     251 2155.58
   262.9  2160.9   272.2 2164.48     277 2165.56   288.4 2167.54   317.9 2171.48
   351.2 2173.86   380.3 2177.13   401.1  2180.6   405.2 2181.98   411.3 2185.01
#Mann= 4 ,-1 , 0
       0      .1       0  172.67      .1       0   172.7    .045       0
   195.1      .1       0
Bank Sta=172.7,195.1
XS Rating Curve= 0 ,0
Exp/Cntr=0.3,0.1

Type RM Length L Ch R = 1 ,7906    ,140.2,139.7,139.3
XS GIS Cut Line= 2
2195332.99227331378643.2369844652195568.88504774378963.604874068
#Sta/Elev= 30
       0 2235.47    12.6 2226.08    16.8 2222.32    43.1 2203.94    61.1 2188.19
    87.7 2167.87    99.8 2155.39   106.5 2149.51   111.3 2148.46   127.5 2150.12
     137 2147.15   139.8 2146.54   146.3 2147.03   158.1 2149.39   174.5 2150.84
   177.3 2150.84   188.4 2148.69     205 2147.91   223.8 2148.33   237.9 2150.52
   242.6 2151.72   253.9 2157.33   261.3  2160.3   280.1 2166.12   296.5 2168.57
   315.3 2170.13   324.7 2171.64   364.6 2180.18   376.2  2184.3   397.8    2194
#Mann= 5 ,-1 , 0
       0      .1       0  136.24      .1       0     137    .045       0
   146.3      .1       0  152.26      .1       0
Bank Sta=137,146.3
XS Rating Curve= 0 ,0
Exp/Cntr=0.3,0.1