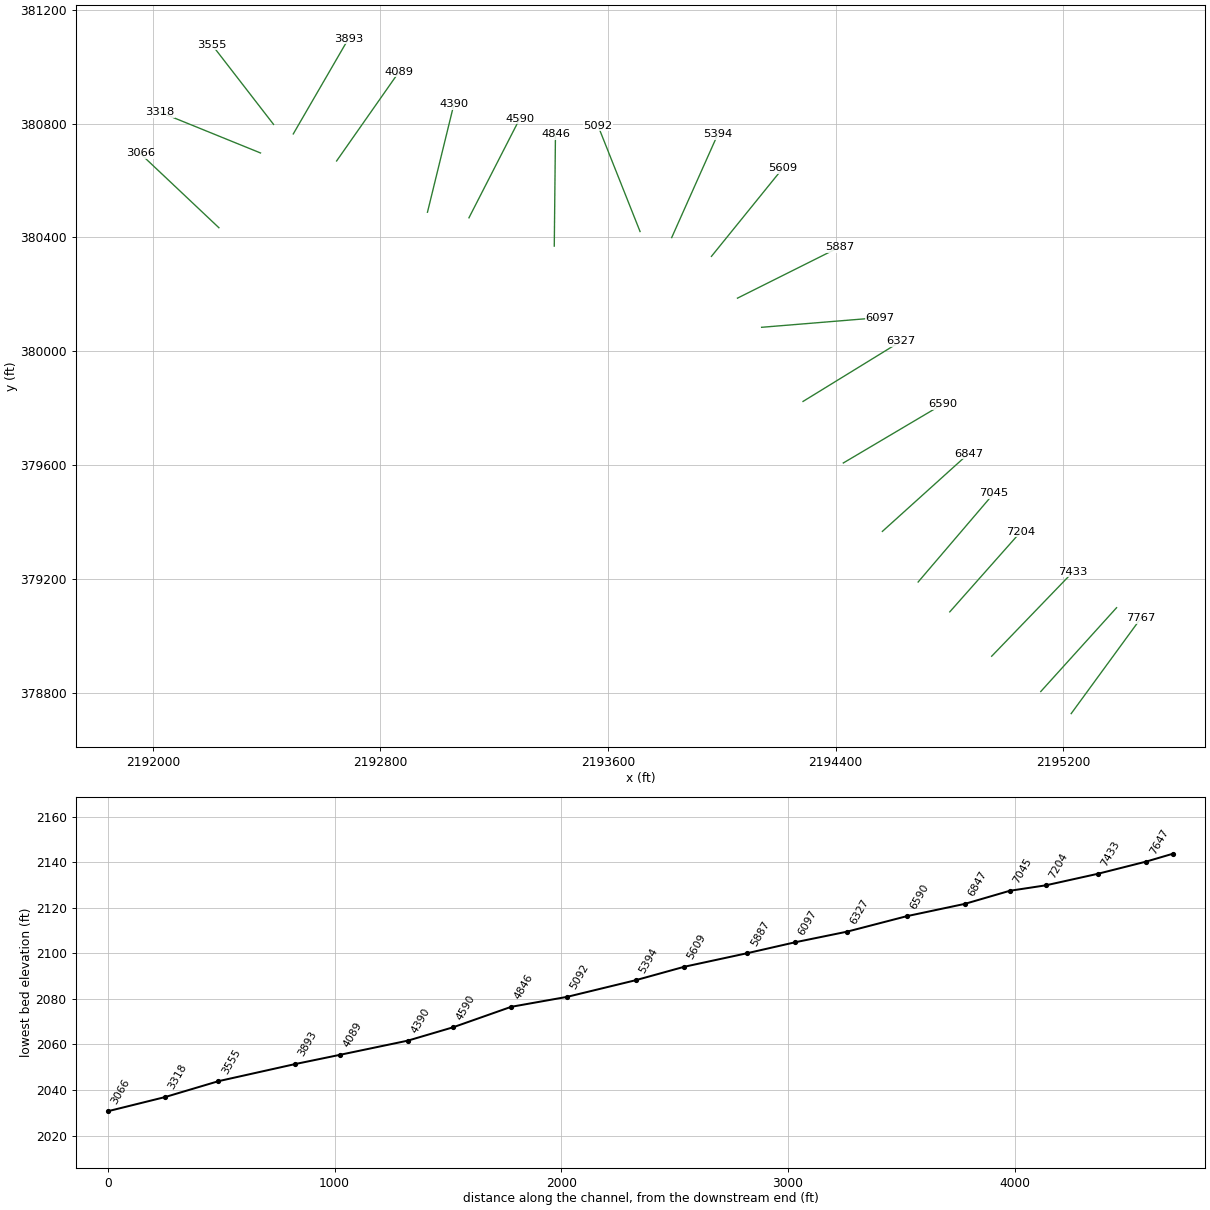
HEC-RAS study SPICERN.prj: SPICERN

--- SPICERN.g01 (geometry) --- (continued)

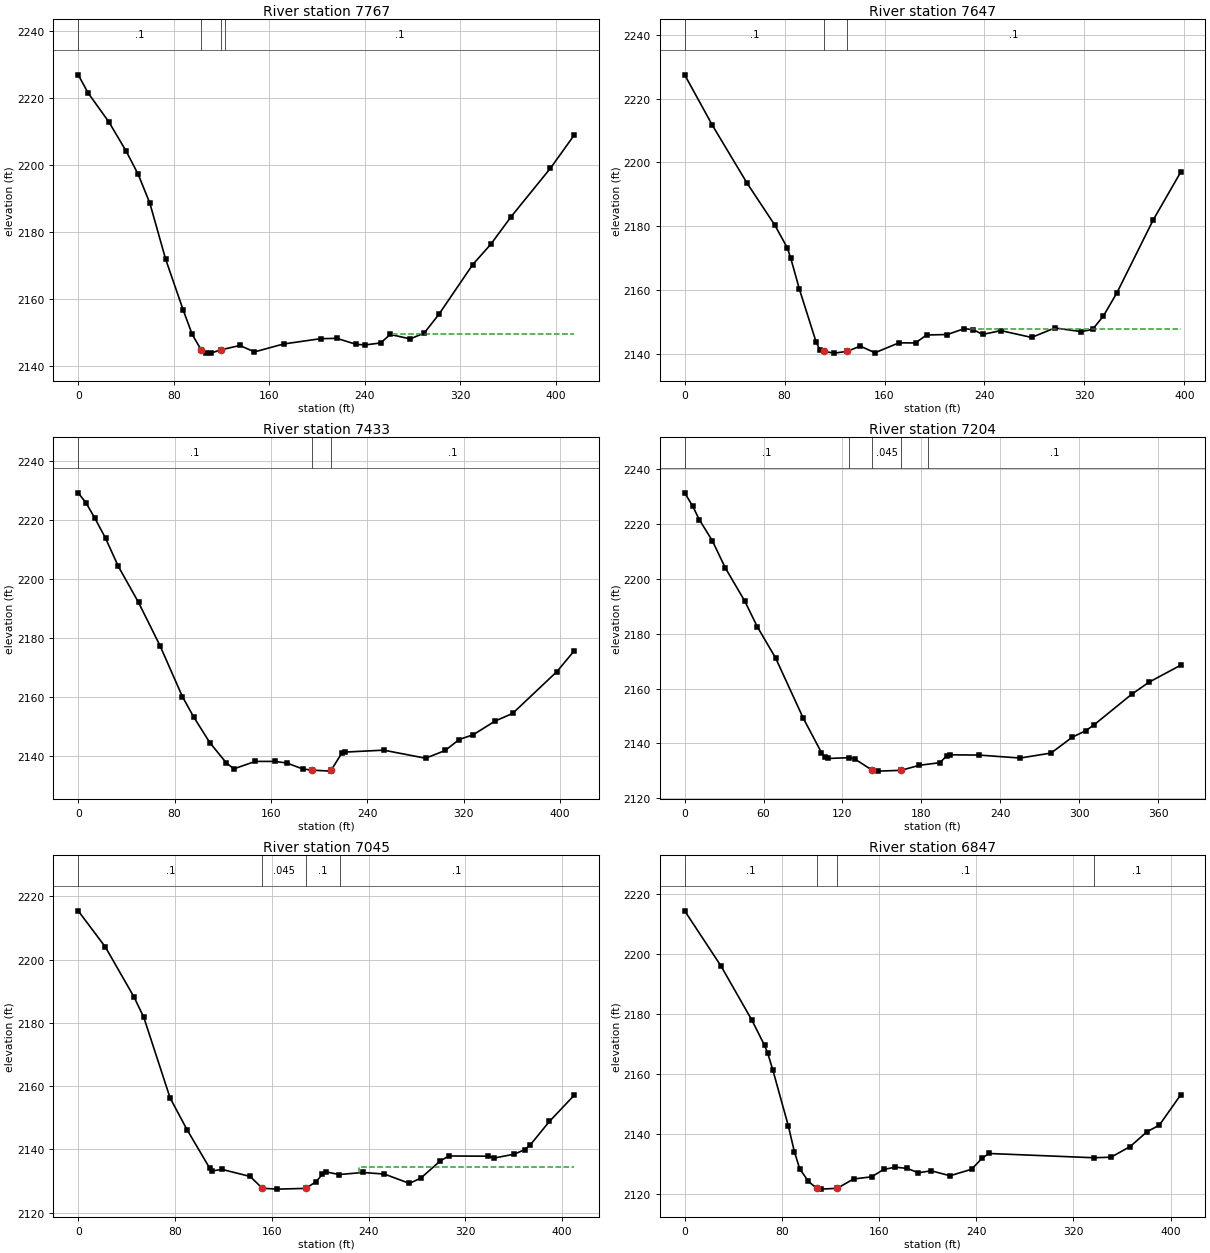
Type RM Length L Ch R = 1 ,7767    ,121.1,120,119.4
XS GIS Cut Line= 2
2195227.52784203378728.4592846922195472.83065351379063.949947277
#Sta/Elev= 30
       0 2226.78     8.3 2221.37    25.8 2212.66      40 2204.13    50.2 2197.14
      60 2188.51    73.3 2171.74    88.1 2156.49    95.5 2149.37     103 2144.75
   106.9 2143.85   111.2 2143.76   119.3 2144.72   135.5 2146.04   147.7 2144.12
   172.1 2146.49   203.2 2148.07   216.8 2148.17   233.1 2146.35   240.7 2146.22
   253.4 2146.79   261.5 2149.33   278.3    2148     290 2149.77   302.2 2155.31
   330.6 2170.17   345.7 2176.21   362.8 2184.47   395.7  2198.9   415.6 2208.78
#Mann= 4 ,-1 , 0
       0      .1       0     103    .045       0   119.3      .1       0
  123.28      .1       0
#XS Ineff= 2 , 0
                          263.63         2149.35
Permanent Ineff=
       F       F
Bank Sta=103,119.3
XS Rating Curve= 0 ,0
Exp/Cntr=0.3,0.1

Type RM Length L Ch R = 1 ,7647    ,214.1,213.7,213
XS GIS Cut Line= 2
2195120.57416623  378805.85665472195386.93640738379100.188706473
#Sta/Elev= 30
       0 2227.42    22.2  2211.6      50 2193.45    72.3 2180.26    82.1 2173.26
    84.9    2170    91.9 2160.19   105.1 2143.88   108.1 2141.35   111.4 2140.81
   119.7 2140.25   129.92140.797   140.6 2142.44   152.3 2140.36   171.5 2143.47
   184.8 2143.44   193.6 2145.93   210.3 2146.08   223.9 2147.93   231.2 2147.56
   238.5 2146.11   253.2  2147.3   277.7 2145.16   296.3 2148.13   317.5 2146.99
   326.5 2147.69   335.2 2151.87   346.1 2159.22     375 2181.93     397  2196.9
#Mann= 3 ,-1 , 0
       0      .1       0   111.4    .045       0   129.9      .1       0
#XS Ineff= 2 , 0
                          228.02          2147.8
Permanent Ineff=
       F       F
Bank Sta=111.4,129.9
XS Rating Curve= 0 ,0
Exp/Cntr=0.3,0.1

Type RM Length L Ch R = 1 ,7433    ,227.9,228.5,227.6
XS GIS Cut Line= 2
2194948.07768563378929.8072238932195234.12129336379226.193249035
#Sta/Elev= 30
       0 2229.11     6.5 2225.68    13.6  2220.7    22.7 2213.74    33.3 2204.22
    50.1 2191.99    67.9 2177.38    86.5 2160.14    95.9 2153.23   109.3 2144.53
     123 2137.67   129.3 2135.65     147 2138.17   163.2 2138.17   173.2 2137.64
   186.4 2135.63   193.92135.218   209.6 2134.88   210.22135.262   218.8 2140.89
   221.2 2141.32   253.7 2141.98   288.5 2139.25   304.8 2141.87   316.4 2145.58
     328 2147.19   346.4 2151.87   360.8 2154.42   397.6 2168.59   411.9 2175.58
#Mann= 3 ,-1 , 0
       0      .1       0   193.9    .045       0   210.2      .1       0
#XS Ineff= 2 , 0
                          242.65         2140.35
Permanent Ineff=
       F       F
Bank Sta=193.9,210.2
XS Rating Curve= 0 ,0
Exp/Cntr=0.3,0.1

Type RM Length L Ch R = 1 ,7204    ,158.1,159.7,160.7
XS GIS Cut Line= 2
2194800.82332259379085.521606956 2195051.0609279379367.636614219
#Sta/Elev= 30
       0 2231.43     6.2 2226.47    11.1 2221.65      21 2213.97    30.9 2204.02
    45.7  2191.9    55.2 2182.57    69.2 2171.08    90.2 2149.13     104 2136.62
   106.4 2135.16   108.7 2134.45     125 2134.75   129.6 2134.21   142.6 2130.16
     147 2129.84   164.5 2130.13   178.4 2131.96   194.1 2132.93   199.3 2135.45
   201.6  2135.8   223.7  2135.7   255.1 2134.62   278.6 2136.44   294.6 2142.19
   304.9 2144.59   310.9 2146.59   339.9  2157.9   353.1 2162.32   377.1 2168.49
#Mann= 5 ,-1 , 0
       0      .1       0   125.2      .1       0   142.6    .045       0
   164.5      .1       0   185.2      .1       0
Bank Sta=142.6,164.5
XS Rating Curve= 0 ,0
Exp/Cntr=0.3,0.1

Type RM Length L Ch R = 1 ,7045    ,198,197.7,196.3
XS GIS Cut Line= 2
2194689.65678689379190.4024693222194956.04362024379502.078638607
#Sta/Elev= 30
       0 2215.39    22.5 2203.92    46.1 2188.17    54.2 2181.74      76 2156.21
      90  2146.2   108.6 2134.12     111 2133.19   118.9 2133.66   142.1 2131.44
   152.2 2127.71   164.5 2127.43     188 2127.66   196.6 2129.76   201.7 2132.06
   205.2 2132.86   215.7 2132.04   235.4 2132.69   253.1 2132.19   273.8 2129.24
   283.2 2130.91   299.4 2136.36   306.4 2137.91     339 2137.84     344 2137.27
   360.6 2138.48   369.3 2139.94   373.9 2141.48   389.5 2148.81     410 2157.08
#Mann= 4 ,-1 , 0
       0      .1       0   152.2    .045       0     188      .1       0
  216.26      .1       0
#XS Ineff= 2 , 0
                          232.12         2134.46
Permanent Ineff=
       F       F
Bank Sta=152.2,188
XS Rating Curve= 0 ,0
Exp/Cntr=0.3,0.1

Type RM Length L Ch R = 1 ,6847    ,257.9,257,255
XS GIS Cut Line= 2
2194563.97624081379368.0547466322194867.17031301379641.376076139
#Sta/Elev= 30
       0 2214.46    29.8 2196.12    55.4 2177.96    65.7 2169.65    68.2 2167.22
    72.6 2161.33    85.3 2142.79    90.3 2134.16    94.7 2128.45   101.8 2124.31
   108.52122.005   112.4  2121.7   125.6 2121.98     139 2125.09   153.9  2125.8
   163.7 2128.25   173.5 2129.03   183.3 2128.58   192.4 2127.15   202.9 2127.81
   218.4 2126.16   236.1 2128.31   244.9 2132.04   250.5 2133.58   336.5 2132.16
   350.9 2132.34   366.7  2135.9   380.6 2140.85   390.7 2143.03   408.2 2153.08
#Mann= 4 ,-1 , 0
       0      .1       0   108.5    .045       0   125.6      .1       0
   336.5      .1       0
#XS Ineff= 2 , 0
                          173.89         2127.94
Permanent Ineff=
       F       F
Bank Sta=108.5,125.6
XS Rating Curve= 0 ,0
Exp/Cntr=0.3,0.1

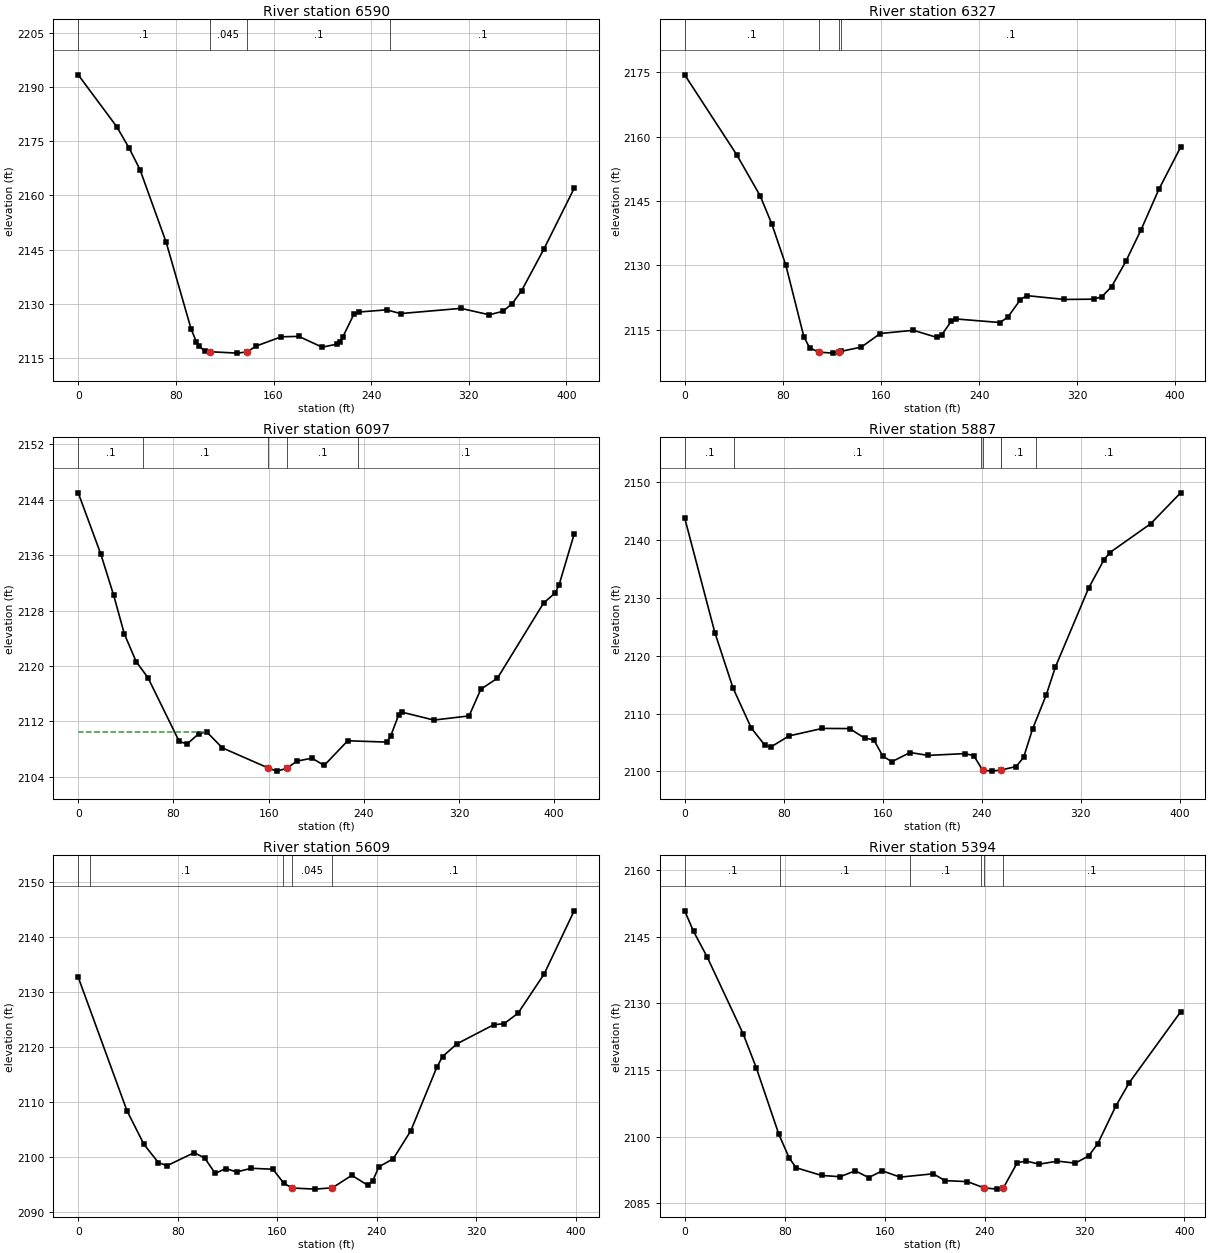
Type RM Length L Ch R = 1 ,6590    ,261.3,262.8,263
XS GIS Cut Line= 2
2194426.70451854379608.2709367632194776.44162352379815.074093067
#Sta/Elev= 30
       0 2193.43    31.6 2179.03    41.8 2173.06    50.6 2167.16    72.1 2146.96
    92.5 2122.95    96.9 2119.35    99.3 2118.15   104.1 2116.76   107.8 2116.67
   130.4 2116.28   138.3 2116.62   145.9 2118.26   166.4 2120.81   180.7 2120.92
   199.9 2117.93   211.9 2118.77   214.3 2119.31   216.7 2120.72   225.9  2127.1
   229.8 2127.67   252.6 2128.28   264.1 2127.25   313.6 2128.69   336.7 2126.91
   347.9 2127.87   355.6 2130.01   363.2 2133.57   381.5 2145.12   406.3 2161.97
#Mann= 4 ,-1 , 0
       0      .1       0   107.8    .045       0   138.3      .1       0
  255.82      .1       0
Bank Sta=107.8,138.3
XS Rating Curve= 0 ,0
Exp/Cntr=0.3,0.1

Type RM Length L Ch R = 1 ,6327    ,233.7,229.7,226.1
XS GIS Cut Line= 2
2194285.12589811  379824.31906642194629.76606765380035.899736861
#Sta/Elev= 30
       0 2174.45    42.4 2155.81    61.5 2146.24      71 2139.68    82.5 2130.01
    97.2 2113.32   101.8 2110.78   109.2 2109.73     121  2109.5   125.9 2109.72
   127.5 2109.91   144.1 2110.92   159.5 2114.08   186.5 2114.83   205.7 2113.16
   209.6 2113.76   217.3 2116.92   221.1 2117.48   257.1 2116.64   263.5  2117.9
   273.8 2121.99   278.9 2122.92   309.6 2122.03   333.4 2122.09   340.1 2122.65
   348.1    2125   359.7  2130.9   372.1 2138.26   386.6 2147.69   404.4 2157.57
#Mann= 4 ,-1 , 0
       0      .1       0   109.2    .045       0   125.9      .1       0
   127.5      .1       0
Bank Sta=109.2,125.9
XS Rating Curve= 0 ,0
Exp/Cntr=0.3,0.1

Type RM Length L Ch R = 1 ,6097    ,207.3,210.4,213
XS GIS Cut Line= 2
2194139.58923267 380084.588775182194554.99296228380118.694958708
#Sta/Elev= 30
       0    2145    19.1  2136.1    29.8 2130.21    38.8 2124.62    48.7 2120.64
    58.6 2118.32    84.9 2109.11    91.5 2108.75   101.4 2110.24     108 2110.49
   121.1 2108.19   159.22105.321   166.7 2104.83   175.32105.228   183.7 2106.27
   196.5  2106.7   206.7 2105.65   226.5 2109.21   259.4 2109.02   262.7 2109.94
   269.3 2112.93   272.5 2113.32   298.9  2112.2   328.5  2112.8   338.4 2116.66
   352.3 2118.24   391.1 2129.09   400.9 2130.56   404.2 2131.75   416.8 2139.04
#Mann= 5 ,-1 , 0
       0      .1       0   54.07      .1       0   159.2    .045       0
   175.3      .1       0  235.42      .1       0
#XS Ineff= 2 , 0
           108.6 2110.53
Permanent Ineff=
       F       F
Bank Sta=159.2,175.3
XS Rating Curve= 0 ,0
Exp/Cntr=0.3,0.1

Type RM Length L Ch R = 1 ,5887    ,274.6,278.3,281.3
XS GIS Cut Line= 2
2194054.73035717380186.9070969482194413.20131079380365.968193207
#Sta/Elev= 30
       0 2143.86    24.4 2124.01    39.1 2114.42    53.8 2107.52    64.7 2104.56
    69.6 2104.24    84.3 2106.15   111.2 2107.45   133.2 2107.42   145.4 2105.78
   152.8 2105.47   160.1 2102.65   167.4 2101.69   182.1 2103.28   196.7 2102.78
   226.2 2103.09   233.5 2102.75   240.7 2100.24   248.1 2100.06   255.72100.253
   267.7 2100.85   273.8 2102.42   281.1 2107.36     292 2113.18   299.6 2118.11
   326.4 2131.74   338.7 2136.59   343.5 2137.87   376.5 2142.86   400.7 2148.21
#Mann= 7 ,-1 , 0
       0      .1       0   39.88      .1       0  239.63      .1       0
   240.7    .045       0   255.7      .1       0  255.72      .1       0
  284.19      .1       0
#XS Ineff= 2 , 0
          119.18 2107.18
Permanent Ineff=
       F       F
Bank Sta=240.7,255.7
XS Rating Curve= 0 ,0
Exp/Cntr=0.3,0.1

Type RM Length L Ch R = 1 ,5609    ,213.9,214.4,216.3
XS GIS Cut Line= 2
2193963.28830977380333.6316664412194214.41284881380643.440738599
#Sta/Elev= 30
       0 2132.64    39.2 2108.35    52.8 2102.26    64.4 2098.93    71.4 2098.35
    93.3 2100.73   101.8 2099.72   110.2 2096.94   118.6 2097.84   127.4 2097.21
   139.1 2097.88   156.6 2097.71   165.1 2095.22   171.7  2094.3   190.3 2094.09
   204.4 2094.33     220  2096.6   232.7 2094.82   236.9 2095.61   241.7 2098.13
   253.4 2099.63   267.4 2104.68   288.4 2116.28     293  2118.2   304.5 2120.51
     334 2123.98   342.5 2124.19   353.7 2126.09   374.7 2133.23   398.8 2144.71
#Mann= 5 ,-1 , 0
       0      .1       0     9.3      .1       0  164.29      .1       0
   171.7    .045       0   204.4      .1       0
#XS Ineff= 2 , 0
           93.31  2100.7
Permanent Ineff=
       F       F
Bank Sta=171.7,204.4
XS Rating Curve= 0 ,0
Exp/Cntr=0.3,0.1

Type RM Length L Ch R = 1 ,5394    ,296.9,302.4,311.3
XS GIS Cut Line= 2
2193823.64477603380399.5835206932193985.50923669380761.982790527
#Sta/Elev= 30
       0 2150.78     7.1 2146.15    17.9 2140.45    46.7 2123.18    57.3 2115.49
    75.4 2100.49    83.7 2095.16    89.2    2093   109.5 2091.27   124.4 2090.98
   136.5 2092.31   147.3 2090.79   158.1 2092.31   172.4 2090.89   198.9 2091.64
   208.4  2090.1   226.3 2089.88   239.6 2088.47   250.1 2088.19   255.1 2088.49
   266.2 2094.15   273.4  2094.5   283.8  2093.8   298.3 2094.49   312.6 2094.03
   323.4 2095.68   330.6 2098.41   344.9 2106.79   355.7 2112.09   396.9 2128.05
#Mann= 6 ,-1 , 0
       0      .1       0   76.31      .1       0  180.48      .1       0
   236.8      .1       0   239.6    .045       0   255.1      .1       0
Bank Sta=239.6,255.1
XS Rating Curve= 0 ,0
Exp/Cntr=0.3,0.1

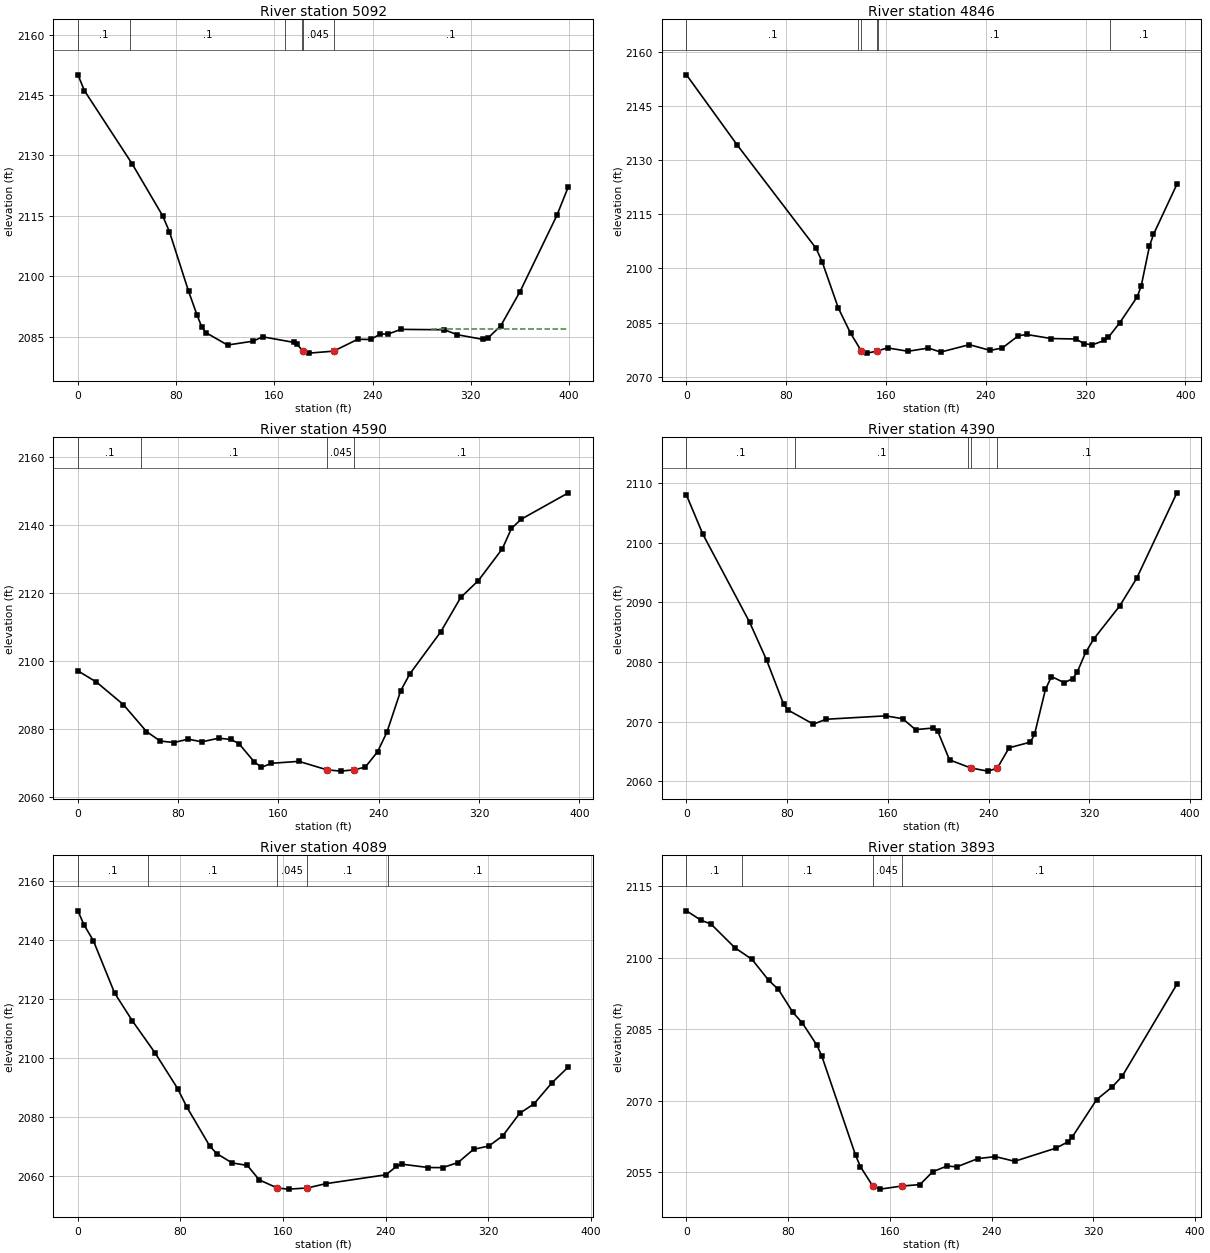
Type RM Length L Ch R = 1 ,5092    ,248.1,246.2,243.2
XS GIS Cut Line= 2
 2193712.4019773380420.854059762 2193564.7644773380791.977230862
#Sta/Elev= 30
       0    2150     5.3 2146.06    44.2 2127.87    68.9 2115.04    74.5 2111.06
    90.1 2096.24    97.1 2090.26   100.7  2087.5   104.2 2085.98   121.8  2082.9
   142.7 2083.86   150.3 2084.95   175.6 2083.57   178.3 2083.19   183.2 2081.36
   188.2 2080.89   208.2 2081.38   227.8 2084.32   238.4 2084.28   246.3 2085.64
   252.5 2085.63   263.1 2086.79   298.4 2086.69     309 2085.46   330.2 2084.28
   333.7 2084.59   344.3 2087.66     360 2096.16     390 2115.07   399.4 2122.25
#Mann= 6 ,-1 , 0
       0      .1       0   42.29      .1       0   168.5      .1       0
  182.86      .1       0   183.2    .045       0   208.2      .1       0
#XS Ineff= 2 , 0
                          288.63          2086.9
Permanent Ineff=
       F       F
Bank Sta=183.2,208.2
XS Rating Curve= 0 ,0
Exp/Cntr=0.3,0.1

Type RM Length L Ch R = 1 ,4846    ,256.2,255.6,252.3
XS GIS Cut Line= 2
2193410.98709025380369.6196167952193415.17132204 380762.80201956
#Sta/Elev= 30
       0 2153.59    40.6  2134.2   103.9 2105.56   108.7  2101.9   121.8 2088.97
   131.6 2082.03   140.1 2077.17   144.8 2076.53   152.6 2077.08   161.2 2077.98
   177.6 2077.05     194 2077.93   203.8 2076.82   226.8 2078.87   243.5 2077.29
   253.2 2077.95   266.1 2081.34   272.7 2081.69   292.4 2080.57   312.1 2080.44
   318.7 2079.17   325.2  2078.8   335.1 2080.04   338.3 2080.92   347.4 2084.96
   361.3 2092.07   364.6 2095.15   371.2 2106.16   374.4 2109.39   393.2 2123.29
#Mann= 6 ,-1 , 0
       0      .1       0  137.76      .1       0   140.1    .045       0
   152.6      .1       0  153.81      .1       0  339.71      .1       0
#XS Ineff= 2 , 0
                          273.57         2081.25
Permanent Ineff=
       F       F
Bank Sta=140.1,152.6
XS Rating Curve= 0 ,0
Exp/Cntr=0.3,0.1

Type RM Length L Ch R = 1 ,4590    ,196.2,199.9,201.4
XS GIS Cut Line= 2
2193111.16268983380469.010360141 2193289.7007586380817.210680649
#Sta/Elev= 30
       0  2097.1    14.8 2093.79    36.2 2087.18    54.7 2079.23    65.7 2076.42
    76.8    2076    87.9 2076.99    98.9  2076.2   112.3 2077.27   122.1 2076.89
   128.4 2075.68   140.5 2070.37   146.4 2068.67   154.2 2069.87   176.3 2070.45
   198.5 2067.97   209.5 2067.57   220.6 2067.96   229.3 2068.77   239.1  2073.3
   246.5 2079.03   257.5 2091.24   264.8 2096.21   289.5 2108.62   305.4 2118.73
   319.5  2123.7   338.6 2133.06   345.9 2139.06   353.6 2141.76   391.3 2149.54
#Mann= 4 ,-1 , 0
       0      .1       0   50.22      .1       0   198.5    .045       0
   220.6      .1       0
Bank Sta=198.5,220.6
XS Rating Curve= 0 ,0
Exp/Cntr=0.3,0.1

Type RM Length L Ch R = 1 ,4390    ,304.8,301.5,295.9
XS GIS Cut Line= 2
2192965.42252192380488.6667664862193058.10896465380866.982857629
#Sta/Elev= 30
       0 2107.99      13 2101.44    50.1 2086.69    63.6 2080.35    77.1 2072.96
    80.5 2071.96   100.8 2069.58   110.9  2070.4   158.2 2070.97   171.7 2070.49
   181.9 2068.66   195.4 2068.92   199.5 2068.42   208.9 2063.59   225.8 2062.23
   239.3  2061.7   246.8 2062.17   256.2 2065.61   273.1 2066.56   276.4 2067.85
   285.1 2075.41   289.9 2077.56   300.1 2076.52   306.8 2077.23   310.2 2078.24
     317  2081.6   323.7 2083.93     344 2089.38   357.5 2094.02   389.5 2108.37
#Mann= 5 ,-1 , 0
       0      .1       0   86.16      .1       0  223.63      .1       0
   225.8    .045       0   246.8      .1       0
Bank Sta=225.8,246.8
XS Rating Curve= 0 ,0
Exp/Cntr=0.3,0.1

Type RM Length L Ch R = 1 ,4089    ,194.6,196,196.4
XS GIS Cut Line= 2
2192646.08744003 380668.577108512192865.78034645  380981.8593016
#Sta/Elev= 30
       0 2150.01     4.7 2145.26      12  2139.9    28.6 2122.07    42.4 2112.66
    60.1 2101.77    77.8 2089.59    84.8 2083.44   102.9 2070.02   108.2 2067.53
   120.2 2064.35   132.2 2063.48   141.4 2058.58   155.52055.813   164.3 2055.43
     179 2055.82   193.2 2057.27   240.3 2060.31   248.4 2063.13   252.5 2063.92
   273.3 2062.77   284.5 2062.74   296.5 2064.46   308.6 2068.95   320.6 2070.09
   331.5 2073.58   344.6  2081.2   355.7 2084.37   369.8 2091.59   382.6 2096.96
#Mann= 5 ,-1 , 0
       0      .1       0   54.51      .1       0   155.5    .045       0
     179      .1       0  241.71      .1       0
Bank Sta=155.5,179
XS Rating Curve= 0 ,0
Exp/Cntr=0.3,0.1

Type RM Length L Ch R = 1 ,3893    ,331.1,338,353
XS GIS Cut Line= 2
2192493.85497879380763.5407588482192687.40652505381097.166027834
#Sta/Elev= 30
       0  2109.8    11.6  2107.8    19.2 2107.05    38.1 2102.05    51.5 2099.63
    64.7 2095.21    72.3 2093.31    83.7  2088.5    91.2 2086.24   102.6  2081.6
   106.4 2079.35     133 2058.51   136.8 2056.12   146.5 2052.06   152.4 2051.41
   169.22052.055   183.6 2052.36   193.7 2055.07     205 2056.26   212.6 2056.08
   229.2 2057.82     243 2058.23   258.1 2057.25   290.4    2060   299.9 2061.31
   303.5 2062.39   322.6  2070.2   334.8 2072.85   342.7  2075.1   385.7  2094.4
#Mann= 4 ,-1 , 0
       0      .1       0   43.97      .1       0   146.5    .045       0
   169.2      .1       0
Bank Sta=146.5,169.2
XS Rating Curve= 0 ,0
Exp/Cntr=0.3,0.1

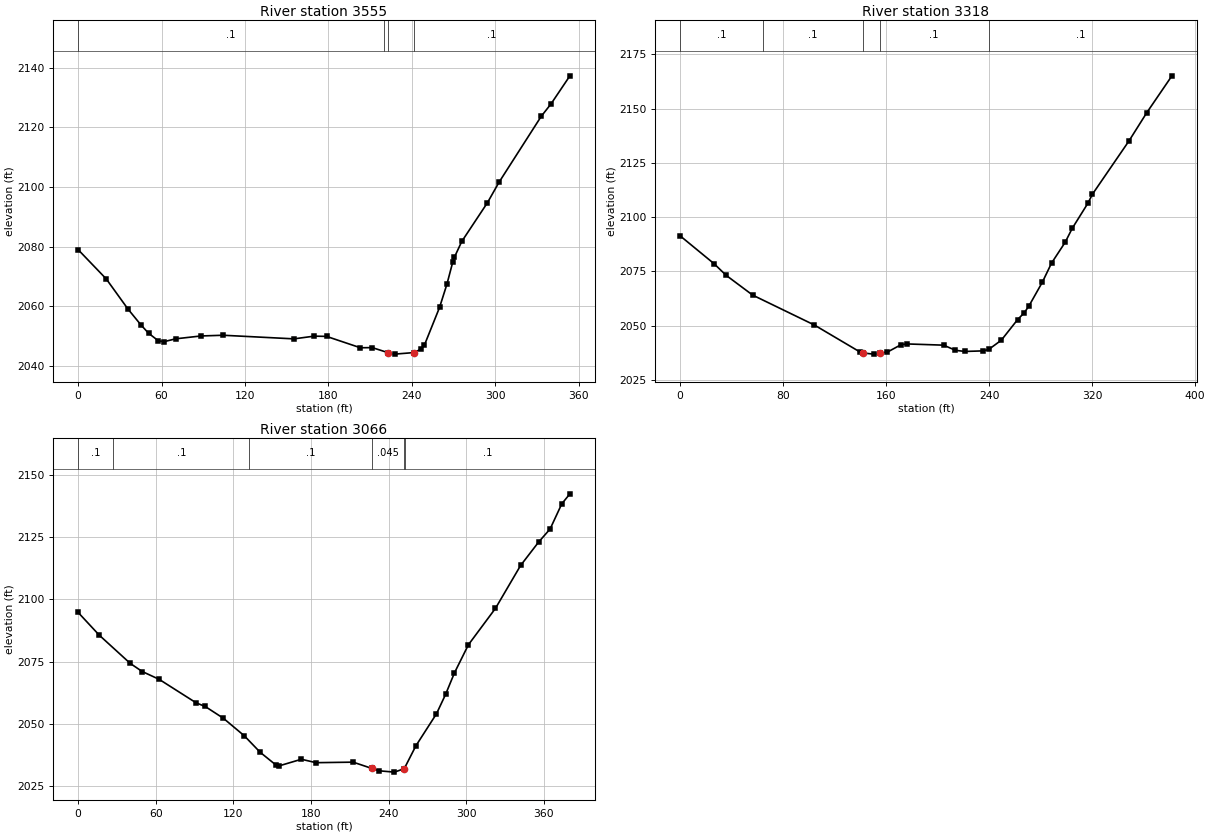
Type RM Length L Ch R = 1 ,3555    ,234.3,236.1,245.5
XS GIS Cut Line= 2
2192424.56110486380796.8598934122192208.15853611381076.420949609
#Sta/Elev= 30
       0 2078.99    20.3 2069.13    35.9 2059.03    45.2 2053.72    50.7 2050.92
    57.7 2048.39    61.8 2048.08    70.1 2049.04    88.3    2050   104.3 2050.24
   155.2 2049.03   169.7 2049.94   178.6 2049.86   202.9 2046.05   211.5 2046.09
     223 2044.37   227.6 2043.91   241.7 2044.44   246.4 2045.61     249    2047
   259.8 2059.55   265.1 2067.34   269.3 2074.77   270.5 2076.41   275.8 2081.71
   294.2 2094.67   302.5 2101.51   332.9 2123.67     340 2127.88   353.5 2137.25
#Mann= 4 ,-1 , 0
       0      .1       0  219.72      .1       0     223    .045       0
   241.7      .1       0
#XS Ineff= 2 , 0
          166.49 2049.29
Permanent Ineff=
       F       F
Bank Sta=223,241.7
XS Rating Curve= 0 ,0
Exp/Cntr=0.3,0.1

Type RM Length L Ch R = 1 ,3318    ,252.4,252.1,250.8
XS GIS Cut Line= 2
2192378.66049759380696.5980224012192024.67473674380840.200026626
#Sta/Elev= 30
       0 2091.46    26.5 2078.55    35.8 2073.23    56.4 2064.12   104.4 2050.31
   139.8 2037.89   142.32037.425   150.4 2036.92     155 2037.39     161 2037.85
   171.6 2041.26   176.1 2041.62   204.7 2041.05   213.9 2038.68   221.2 2038.15
   235.4 2038.42   239.7 2039.07   249.5 2043.33   262.2 2052.86   267.2 2055.91
   270.8 2058.94   281.4  2070.1   288.5 2078.85   299.1 2088.46   304.6 2094.89
   316.8  2106.5   320.3 2110.63   348.7  2135.2   362.5  2148.2     382 2165.15
#Mann= 5 ,-1 , 0
       0      .1       0    64.2      .1       0   142.3    .045       0
     155      .1       0   239.7      .1       0
Bank Sta=142.3,155
XS Rating Curve= 0 ,0
Exp/Cntr=0.3,0.1

Type RM Length L Ch R = 1 ,3066    ,220.9,226.4,226
XS GIS Cut Line= 2
2192232.45692502380434.179506073  2191955.882966380694.921294161
#Sta/Elev= 30
       0  2094.8    16.5 2085.59    40.4 2074.29    49.6 2071.06    62.7 2067.92
    91.3 2058.49    98.3 2057.03   112.3 2052.32   128.5 2045.28   140.8 2038.65
   152.9 2033.58   155.2 2033.19   172.6 2035.87   183.9  2034.5   212.6 2034.71
   226.9 2032.22   232.9 2031.23   244.5 2030.71   252.1  2032.1   261.1 2041.27
     277 2054.11     284 2061.84   290.9 2070.53   301.7 2081.81   322.6  2096.4
     342 2113.58     356 2123.02   364.8 2128.21   373.8 2138.28   380.1 2142.31
#Mann= 6 ,-1 , 0
       0      .1       0   27.31      .1       0  132.33      .1       0
   226.9    .045       0   252.1      .1       0  252.86      .1       0
Bank Sta=226.9,252.1
XS Rating Curve= 0 ,0
Exp/Cntr=0.3,0.1