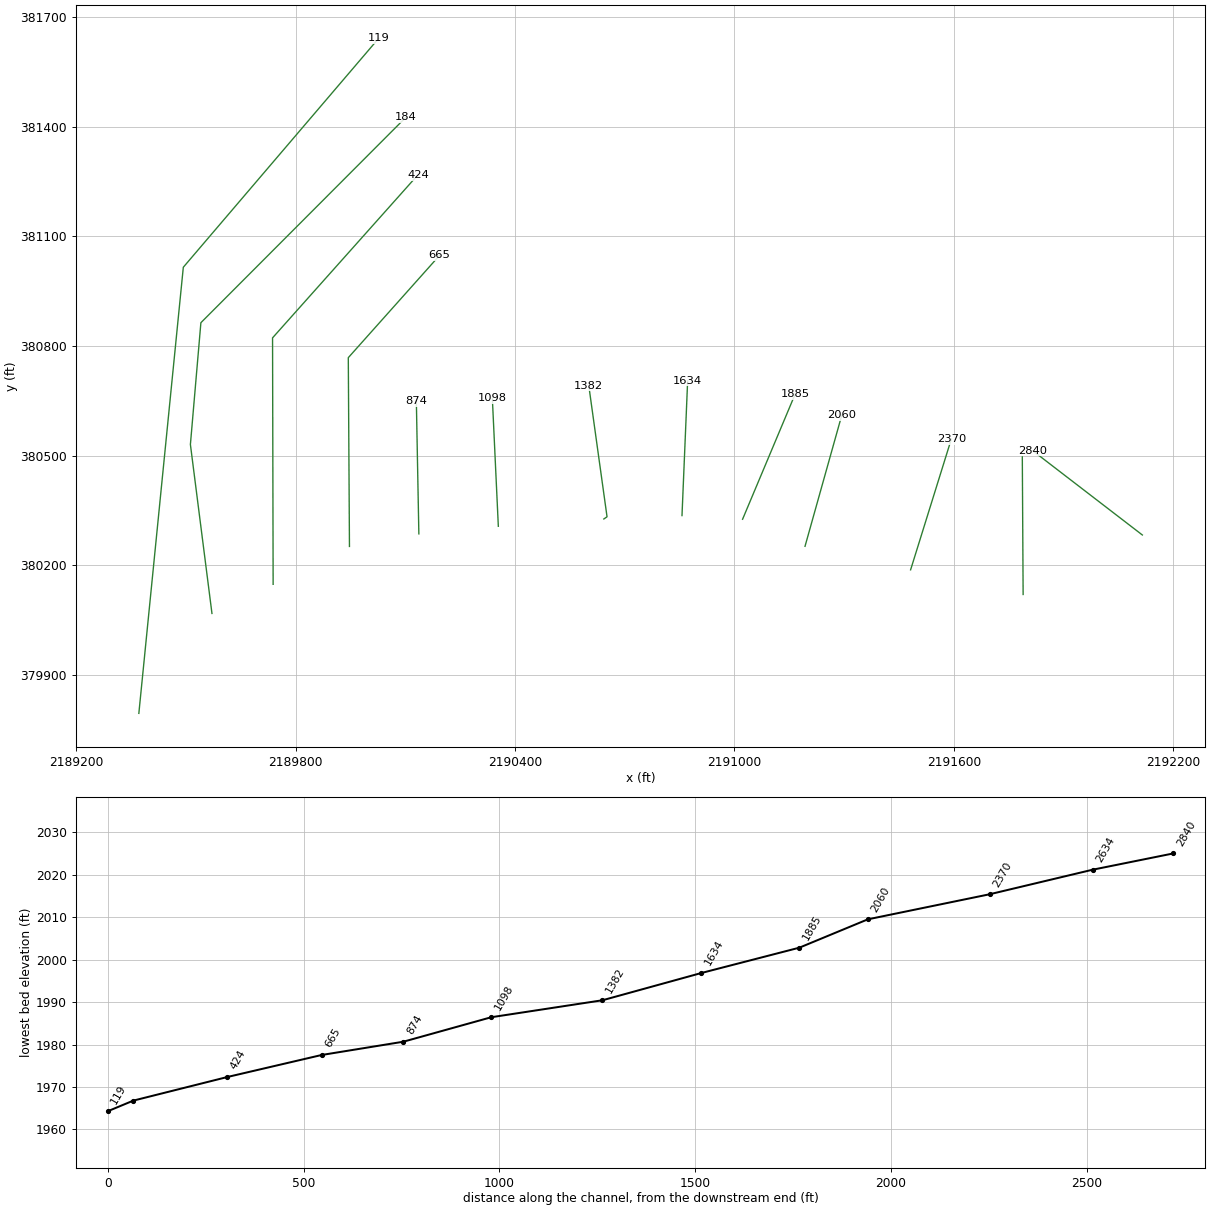
HEC-RAS study SPICERN.prj: SPICERN

--- SPICERN.g01 (geometry) --- (continued)

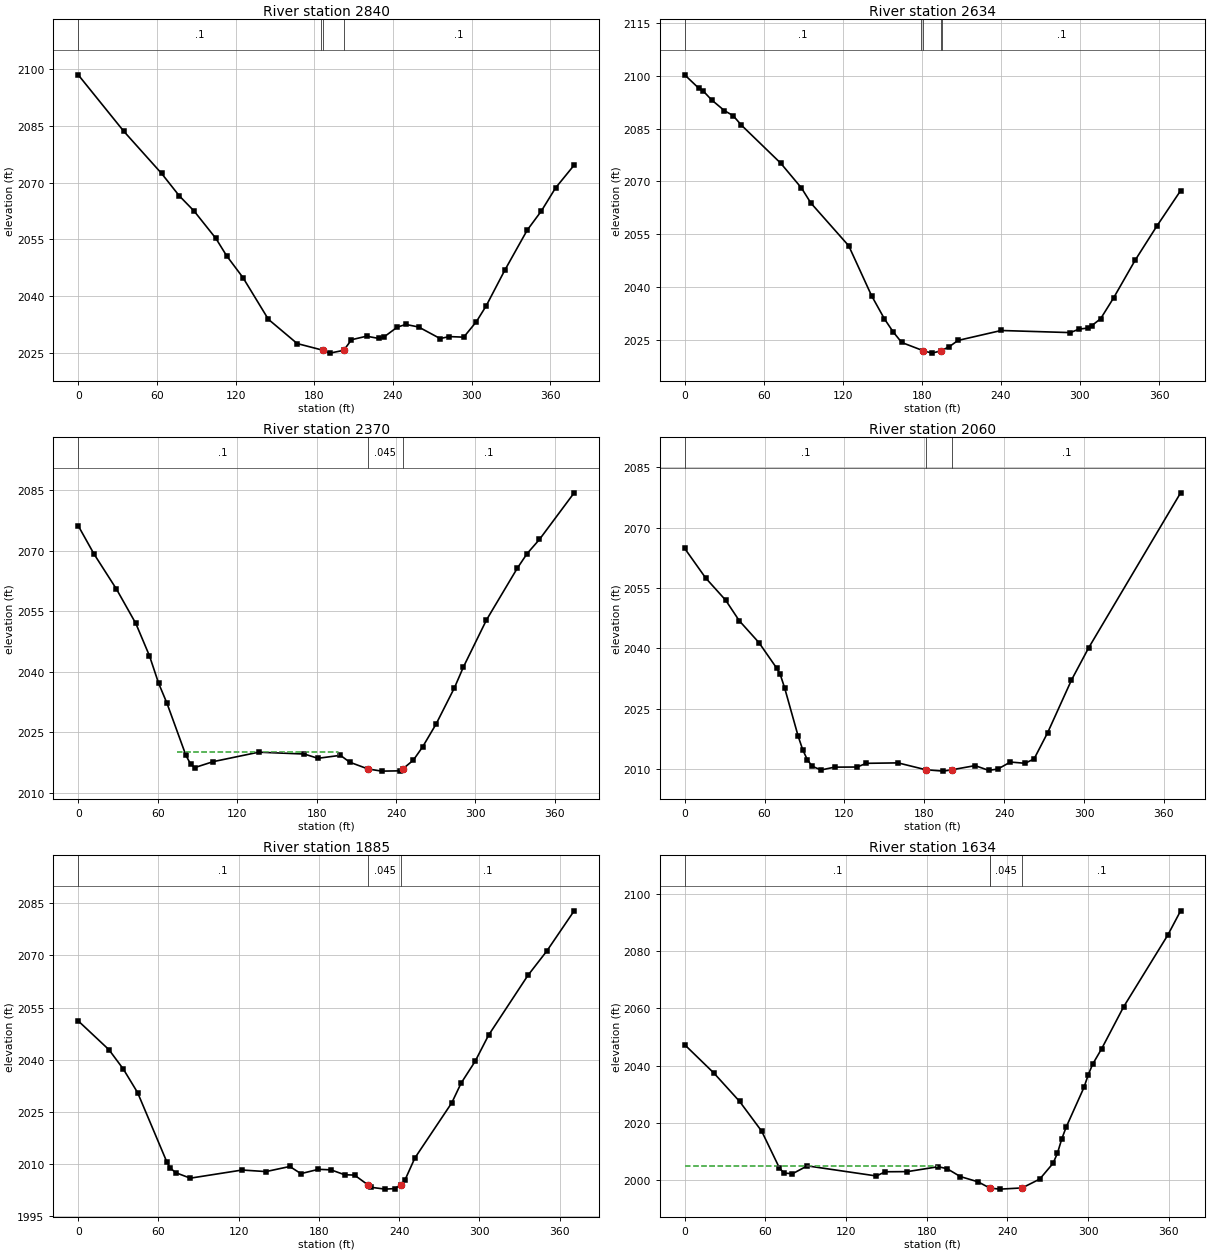
Type RM Length L Ch R = 1 ,2840    ,212.1,206.3,198.7
XS GIS Cut Line= 2
2192115.82909394380282.7191319132191815.97070332 380513.20466492
#Sta/Elev= 30
       0 2098.39    34.6 2083.57    63.6 2072.38    77.1 2066.48    88.4 2062.47
     105 2055.26   113.2 2050.68   125.6 2044.96     145 2033.95     167 2027.55
   186.3 2025.82   191.9 2025.03   202.5 2025.77   208.4 2028.56   219.9 2029.49
   229.4 2028.89   233.2 2029.29   243.3 2031.88   249.8 2032.59   259.6 2031.92
     276 2028.87     283 2029.39     294 2029.24   303.6  2033.3   311.1 2037.48
   325.2 2046.82   342.4 2057.45   353.2  2062.5     364 2068.57   378.2 2074.59
#Mann= 4 ,-1 , 0
       0      .1       0   185.2      .1       0   186.3    .045       0
   202.5      .1       0
Bank Sta=186.3,202.5
XS Rating Curve= 0 ,0
Exp/Cntr=0.3,0.1

Type RM Length L Ch R = 1 ,2634    ,264.3,263.3,262.4
XS GIS Cut Line= 2
2191789.65983645380119.9772441162191787.42499902380496.375058759
#Sta/Elev= 30
       0 2100.25    10.5 2096.51    13.8 2095.76    20.4 2093.14    30.2 2090.06
    36.8 2088.65    42.9 2086.01    72.9 2075.14    88.6 2068.12    95.8 2063.82
   124.5 2051.68   141.8 2037.54   151.6 2030.92   158.2 2027.24   164.7 2024.22
   181.1 2021.87   187.7 2021.19   194.3 2021.81   200.8 2023.01   207.4 2024.79
   240.2 2027.62   292.7 2027.02   299.3 2028.01   305.8  2028.3   309.1 2029.03
   315.7 2030.97   325.5 2036.86   341.9 2047.59   358.3 2057.25   376.4 2067.35
#Mann= 5 ,-1 , 0
       0      .1       0  179.45      .1       0   181.1    .045       0
   194.3      .1       0  195.48      .1       0
Bank Sta=181.1,194.3
XS Rating Curve= 0 ,0
Exp/Cntr=0.3,0.1

Type RM Length L Ch R = 1 ,2370    ,309.7,310.7,311.8
XS GIS Cut Line= 2
2191481.81879554380187.3833682972191593.17571825380544.949034925
#Sta/Elev= 30
       0 2076.26    11.9 2069.26    28.9 2060.53    43.5 2052.02    53.8    2044
    60.7  2037.2      67 2032.25    81.3 2019.33    84.8 2017.19    87.9 2016.27
   101.9 2017.75   136.3  2020.1   170.7 2019.64     181 2018.58     198 2019.32
     205 2017.62   218.8 2015.94   229.1  2015.4   242.8 2015.47   245.1 2015.95
     253  2018.1     260 2021.37   270.3 2027.11   284.1 2036.07   290.9 2041.24
   308.3  2052.9   331.6 2065.74     339 2069.36   348.3 2072.86   374.5 2084.42
#Mann= 3 ,-1 , 0
       0      .1       0   218.8    .045       0   245.1      .1       0
#XS Ineff= 2 ,-1
   74.97  136.01 2020.18  139.81  195.86 2020.05
Permanent Ineff=
       F       F
Bank Sta=218.8,245.1
XS Rating Curve= 0 ,0
Exp/Cntr=0.3,0.1

Type RM Length L Ch R = 1 ,2060    ,174.6,174.9,173.8
XS GIS Cut Line= 2
2191193.00622698380251.7718974122191293.59188603380610.542821991
#Sta/Elev= 30
       0 2064.88    15.8 2057.51    30.8    2052      41  2046.9    55.8 2041.45
    69.1 2035.12    71.7 2033.63    75.1 2030.19    85.3 2018.14    88.7  2014.8
    92.1 2012.38    95.7 2010.73   102.4 2009.78   112.6 2010.49   129.6 2010.52
   136.4 2011.44   160.3 2011.55   181.2 2009.84   194.4  2009.5   201.2 2009.86
   218.2 2010.87   228.4 2009.69   235.3 2010.02   244.7 2011.76   255.7 2011.45
   262.5 2012.53   272.7 2019.06   290.6 2032.15   303.4  2040.1   372.6  2078.7
#Mann= 3 ,-1 , 0
       0      .1       0   181.2    .045       0   201.2      .1       0
Bank Sta=181.2,201.2
XS Rating Curve= 0 ,0
Exp/Cntr=0.3,0.1

Type RM Length L Ch R = 1 ,1885    ,246.3,251.1,254.8
XS GIS Cut Line= 2
2191022.22055194380325.8436208032191165.83599705380667.706882616
#Sta/Elev= 30
       0 2051.17      23 2042.88    33.7 2037.34    44.4 2030.56    66.2 2010.69
    68.7 2008.94    72.8 2007.56    83.8 2005.97   122.6 2008.31   140.4 2007.86
   158.2 2009.33   166.5 2007.27   179.6 2008.51     189 2008.36   199.1 2006.96
   206.6 2006.85   216.6 2004.05   219.1 2003.34   229.4 2002.82   236.5 2002.97
   241.7 2004.11   244.2 2005.34   251.7 2011.76   279.3 2027.62   286.3 2033.29
   296.8 2039.57   306.8 2047.05   336.2 2064.23   350.4 2071.27   370.8  2082.8
#Mann= 3 ,-1 , 0
       0      .1       0   216.6    .045       0   241.7      .1       0
Bank Sta=216.6,241.7
XS Rating Curve= 0 ,0
Exp/Cntr=0.3,0.1

Type RM Length L Ch R = 1 ,1634    ,249.3,251.6,253.4
XS GIS Cut Line= 2
2190856.45056414380335.7861562842190871.89226257380704.367193615
#Sta/Elev= 30
       0 2047.31    21.8 2037.37    40.8 2027.52    57.3 2017.07    70.4 2004.31
    73.7 2002.46    80.2 2002.21    91.2 2004.96   142.6 2001.43   149.2  2002.9
   165.6 2002.95   188.6 2004.66   195.2 2003.97     205 2001.23   218.2 1999.38
   227.1 1997.18   234.6 1996.83     251 1997.25   264.1 2000.34     274 2005.84
   277.3 2009.42   280.5 2014.39   283.8 2018.54     297 2032.37   300.2 2036.81
   303.5 2040.54   310.1 2045.85   326.5 2060.56   359.4 2085.67   368.9 2094.12
#Mann= 4 ,-1 , 0
       0      .1       0  227.08      .1       0   227.1    .045       0
     251      .1       0
#XS Ineff= 2 , 0
          187.99 2004.91
Permanent Ineff=
       F       F
Bank Sta=227.1,251
XS Rating Curve= 0 ,0
Exp/Cntr=0.3,0.1

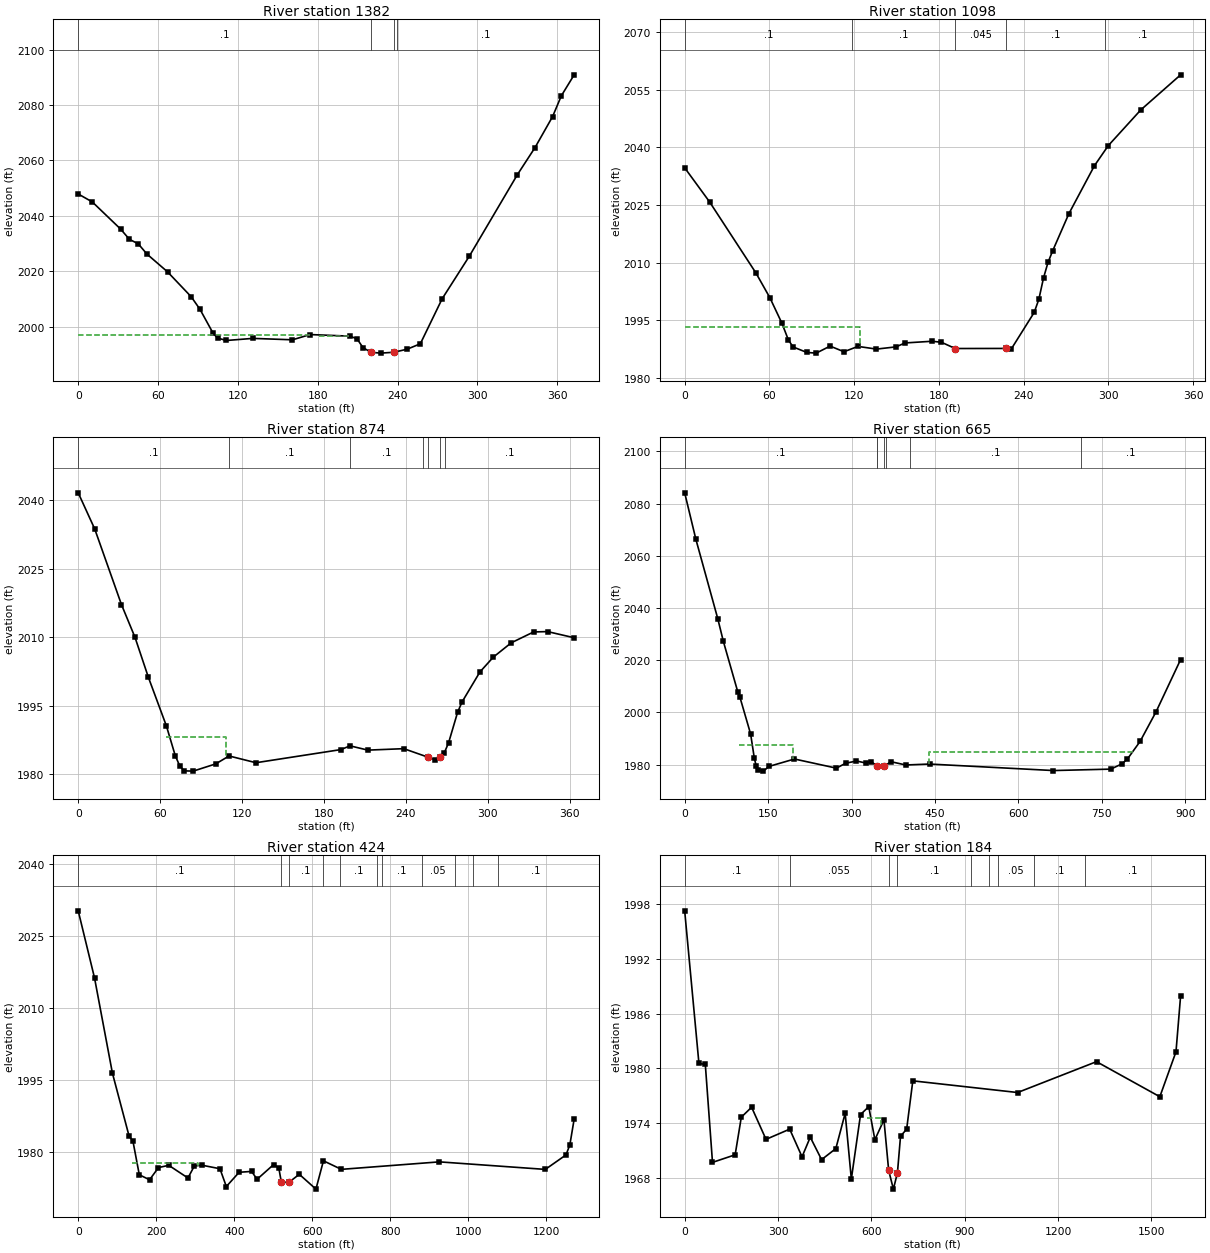
Type RM Length L Ch R = 1 ,1382    ,284.3,284,281.1
XS GIS Cut Line= 3
2190642.69196093380326.511223778 2190651.3844773380332.538674853
2190601.46621547380691.192764913
#Sta/Elev= 30
       0 2047.88    10.6    2045    31.9 2035.19    38.5  2031.5    45.1 2029.89
    51.7 2026.17    67.1 2019.78    84.9 2010.79    91.5 2006.25   101.4 1997.58
   104.7 1995.88   111.4 1994.99   131.2 1995.75     161 1995.24   174.3 1997.13
   204.1 1996.56   209.5 1995.61     214 1992.43     220 1990.73   227.3 1990.43
   237.2 1990.74   247.2 1991.85   257.1  1993.8   273.5 2010.05   293.9 2025.41
     330 2054.82   343.3 2064.64   356.5 2075.82   363.1 2083.35   372.7 2090.89
#Mann= 4 ,-1 , 0
       0      .1       0     220    .045       0   237.2      .1       0
  239.61      .1       0
#XS Ineff= 2 ,-1
       0  174.54 1997.14  180.82  203.68 1996.62
Permanent Ineff=
       F       F
Bank Sta=220,237.2
XS Rating Curve= 0 ,0
Exp/Cntr=0.3,0.1

Type RM Length L Ch R = 1 ,1098    ,225.2,224.6,220.3
XS GIS Cut Line= 2
2190354.01177745380306.5334927922190337.60761079380657.372857883
#Sta/Elev= 30
       0 2034.68    17.6 2025.82    50.4 2007.33    60.3 2000.88    68.9 1994.18
    73.4  1989.9    76.7 1988.05    86.5 1986.61    93.1 1986.43     103 1988.26
   112.8 1986.79   122.7 1988.18   135.8 1987.48   149.7 1988.06     156 1989.08
   175.2 1989.52   181.8 1989.26   191.6 1987.63   227.8 1987.65   231.1  1987.4
   247.5 1997.02   250.8 2000.44   254.1 2005.99   257.3 2010.06   260.6 2013.07
   272.1 2022.75   290.2 2035.24     300 2040.46     323 2049.75   351.2 2058.88
#Mann= 5 ,-1 , 0
       0      .1       0  118.84      .1       0   191.6    .045       0
   227.8      .1       0  297.58      .1       0
#XS Ineff= 2 , 0
          123.94 1993.28
Permanent Ineff=
       F       F
Bank Sta=191.6,227.8
XS Rating Curve= 0 ,0
Exp/Cntr=0.3,0.1

Type RM Length L Ch R = 1 ,874     ,207,208.7,208.6
XS GIS Cut Line= 2
2190136.58778164380285.787452222 2190129.7319773380649.017572737
#Sta/Elev= 30
       0 2041.61    12.1 2033.69    31.7 2017.12    41.6 2009.96    51.4 2001.21
    64.6 1990.56    71.1 1984.04    74.4 1981.79    77.7 1980.72    84.2 1980.66
   100.7 1982.24   110.5 1983.98   130.2  1982.5   192.5 1985.38   199.1  1986.2
   212.2 1985.26   238.5 1985.58   256.1 1983.73   261.4 1983.19   264.7 1983.74
     268 1984.55   271.3 1986.85   277.9 1993.53   281.1 1995.77   294.3 2002.39
   304.1 2005.63   317.2 2008.76   333.6 2011.14   343.8 2011.22   363.3 2009.87
#Mann= 7 ,-1 , 0
       0      .1       0   110.5      .1       0   199.1      .1       0
  252.91      .1       0   256.1    .045       0   264.7      .1       0
  268.96      .1       0
#XS Ineff= 1 ,-1
   63.96  108.12 1988.09
Permanent Ineff=
       F
Bank Sta=256.1,264.7
XS Rating Curve= 0 ,0
Exp/Cntr=0.3,0.1

Type RM Length L Ch R = 1 ,665     ,239.9,240.4,243.8
XS GIS Cut Line= 3
2189946.75220048380251.3773233742189943.56446029380767.791234974
2190193.46992039381047.813624034
#Sta/Elev= 30
       0 2084.11    20.2 2066.25    59.6 2035.84    69.4 2027.33    95.5 2007.87
      99 2006.08   118.6 1991.72   125.2 1982.51   128.5 1979.57   131.8 1977.98
   141.6 1977.53   151.5 1979.33   197.4 1982.17   272.8 1978.67   289.3 1980.54
   308.9 1981.41   325.3 1980.66   335.2 1981.17     3461979.478   358.2 1979.47
   371.3 1981.12   397.5 1979.88   440.2 1980.24     663 1977.75   766.2  1978.3
   786.2 1980.32     796 1982.16   818.8 1988.89   847.6 2000.28   891.7 2020.26
#Mann= 7 ,-1 , 0
       0      .1       0  345.93      .1       0     346    .045       0
   358.2      .1       0  362.05      .1       0  404.98      .1       0
  712.41      .1       0
#XS Ineff= 2 ,-1
   98.49  195.04 1987.56  439.58   805.4 1984.85
Permanent Ineff=
       F       F
Bank Sta=346,358.2
XS Rating Curve= 0 ,0
Exp/Cntr=0.3,0.1

Type RM Length L Ch R = 1 ,424     ,239.9,240.4,238.7
XS GIS Cut Line= 3
2189737.95521771380147.7757670352189736.36134761 380821.98281829
2190133.77945862381267.609811865
#Sta/Elev= 30
       0 2030.33    41.8 2016.35    87.7 1996.51   130.4  1983.4   140.2 1982.38
   156.6 1975.34   182.9  1974.3   205.8 1976.84   232.1 1977.31   281.3 1974.67
   297.7 1977.18   317.4 1977.33   363.3  1976.6   379.7 1972.89   412.5 1975.86
   444.5 1976.04   458.5  1974.4   501.1 1977.48   514.2 1976.76   520.8 1973.75
   540.5 1973.79   566.7 1975.44   609.4 1972.35   628.6 1978.25   674.5 1976.47
   925.8 1978.03  1197.4 1976.46  1250.4 1979.48  1260.3 1981.58  1271.3 1986.94
#Mann= 11 ,-1 , 0
       0      .1       0   520.8    .045       0   540.5      .1       0
   628.6      .1       0  671.87      .1       0  765.82     .05       0
  779.95      .1       0  880.34     .05       0  964.73      .1       0
 1011.21      .1       0 1076.88      .1       0
#XS Ineff= 2 ,-1
  139.12  306.57 1977.76  629.11 1254.17  1978.2
Permanent Ineff=
       F       F
Bank Sta=520.8,540.5
XS Rating Curve= 0 ,0
Exp/Cntr=0.3,0.1

Type RM Length L Ch R = 1 ,184     ,65.2,65.2,64.8
XS GIS Cut Line= 4
2189570.59885747380068.0822621582189511.62566386380530.304590442
2189540.31532561380863.4234408262190100.85264331381425.139097422
#Sta/Elev= 30
       0 1997.26    45.8 1980.55    66.3 1980.44    89.4 1969.71   162.2 1970.54
     182 1974.66   215.1 1975.75   261.4 1972.23   337.5 1973.35   377.2 1970.32
   403.6 1972.47     440 1970.01   485.8 1971.22   515.8 1975.09   535.6 1967.88
   565.2 1974.95   591.6 1975.81   611.3 1972.19   640.4 1974.37   655.6 1968.83
   670.8 1966.78   683.8 1968.57   693.7 1972.57   713.4 1973.35   733.2 1978.64
    1070 1977.36  1323.6 1980.74  1527.1  1976.9    1579 1981.82  1593.9 1987.96
#Mann= 9 ,-1 , 0
       0      .1       0   337.5    .055       0   655.6    .045       0
   683.8      .1       0  920.99     .05       0  978.95      .1       0
 1007.26     .05       0 1121.93      .1       0 1286.96      .1       0
#XS Ineff= 2 ,-1
   55.24   205.4 1975.33  585.14   632.3 1974.62
Permanent Ineff=
       F       F
Bank Sta=655.6,683.8
XS Rating Curve= 0 ,0
Exp/Cntr=0.3,0.1

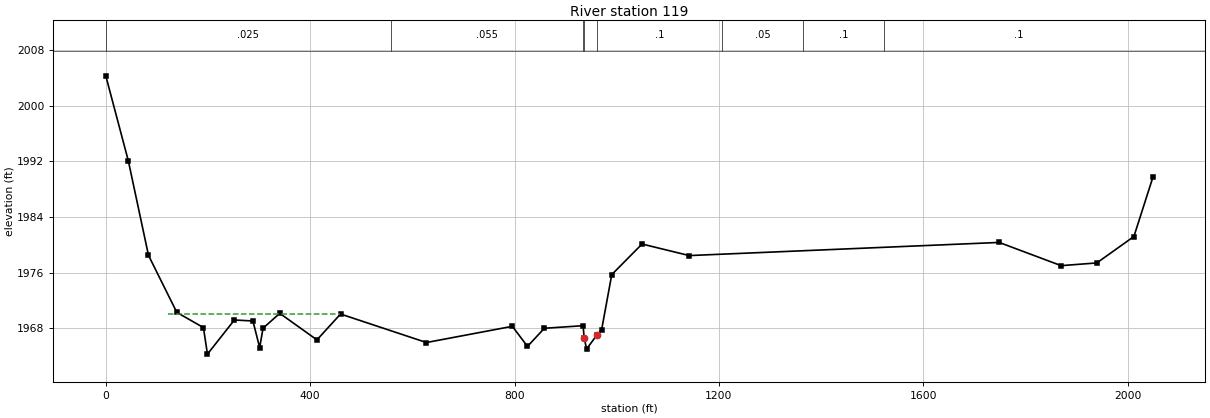
Type RM Length L Ch R = 1 ,119     ,119,119,119
XS GIS Cut Line= 3
2189370.59993418379794.7146589582189492.24818291381015.185613368
2190026.70278386381641.374959259
#Sta/Elev= 30
       0 2004.32    44.2 1992.07    83.6 1978.49     139 1970.29   191.1  1968.1
     199 1964.28   251.7 1969.19     288 1969.05   301.2 1965.22   307.8 1968.01
   340.5 1970.15   413.3 1966.33   459.5 1970.05   627.6 1965.95   795.8 1968.28
   825.4 1965.39   858.4    1968   934.2 1968.37   936.41966.623   941.1 1965.01
   960.6 1966.97   970.5 1967.78   990.3 1975.72  1049.6 1980.12    1142 1978.46
  1748.6 1980.35  1869.9 1977.01  1939.7  1977.4  2012.3  1981.2  2049.8  1989.8
#Mann= 8 ,-1 , 0
       0    .025       0  557.66    .055       0   934.2      .1       0
   936.4    .045       0   960.6      .1       0  1206.1     .05       0
 1364.33      .1       0 1522.56      .1       0
#XS Ineff= 1 ,-1
  120.81  458.76 1970.05
Permanent Ineff=
       F
Bank Sta=936.4,960.6
XS Rating Curve= 0 ,0
Exp/Cntr=0.3,0.1
LCMann Table=0

Chan Stop Cuts=-1
Use User Specified Reach Order=0
Composite Channel Slope=5